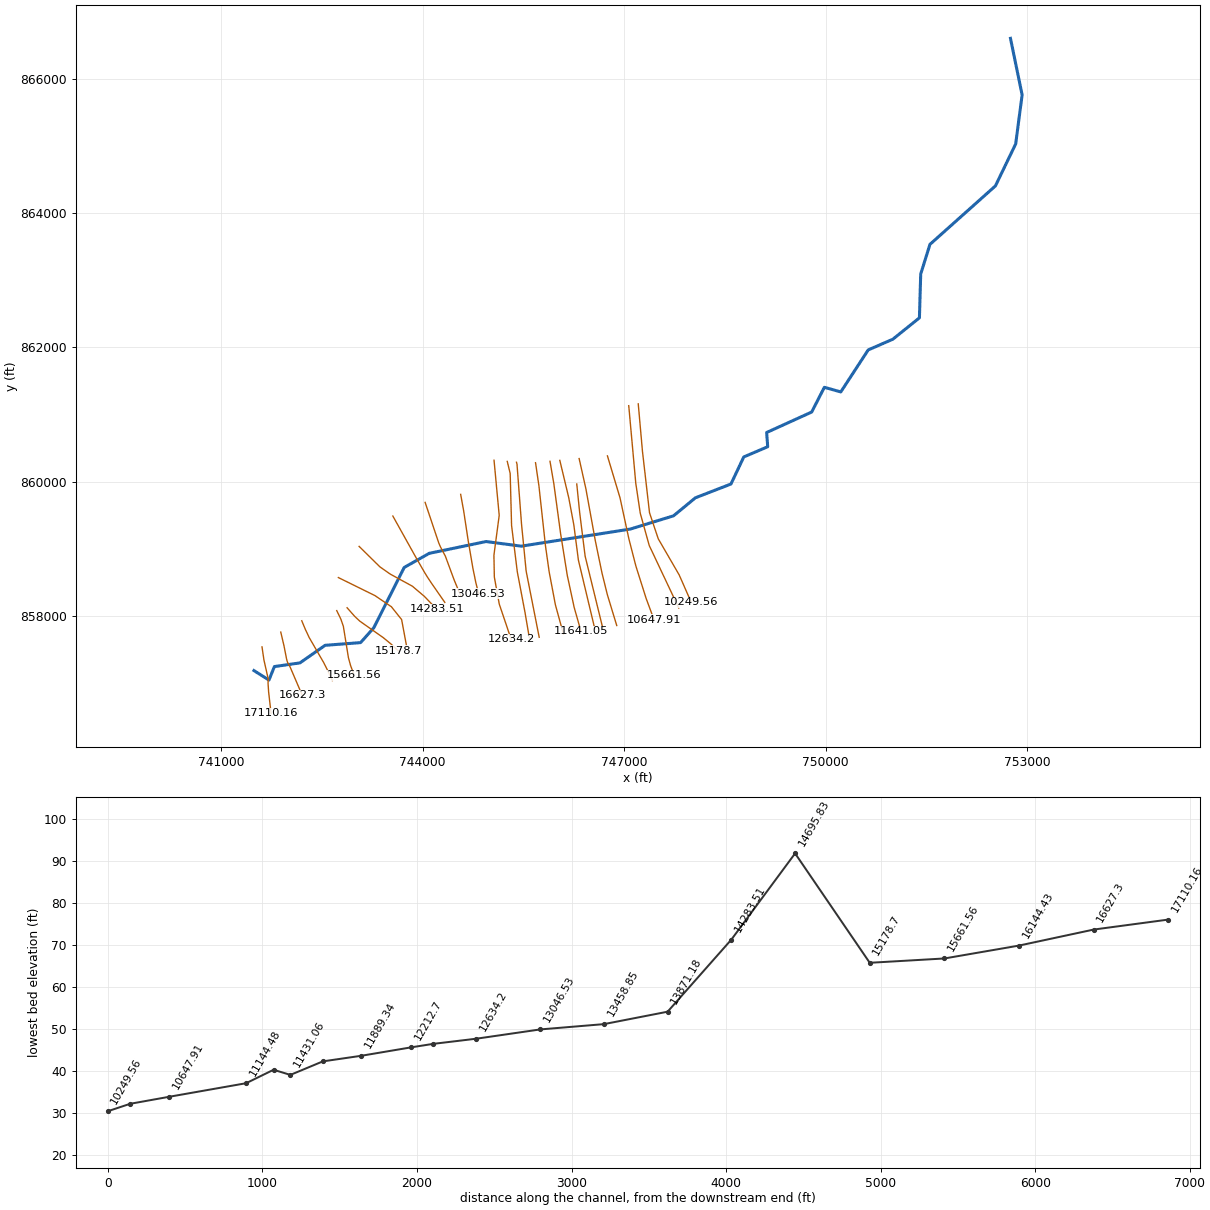
--- 15242_ras.prj (project) ---

Proj Title=15242
Current Plan=p01
Default Exp/Contr=0.3,0.1
English Units
Geom File=g01
Flow File=f01
Plan File=p01
Y Axis Title=Elevation
X Axis Title(PF)=Main Channel Distance
X Axis Title(XS)=Station
BEGIN DESCRIPTION:
RFD model 15242 exported to HEC-RAS
END DESCRIPTION:

--- 15242_ras.p01 (plan) ---

Plan Title=Plan 01
Program Version=4.10
Short Identifier=Plan 01
Geom File=g01
Flow File=f01
Subcritical Flow
Calc Critical at every XS
Secant Critical Depth

--- 15242_ras.f01 (steady flow) ---

Flow Title=Flow 01
Program Version=5.01
Number of Profiles= 6
Profile Names=10yr,25yr,50yr,100yr,100plus,500yr
River Rch & RM=15242,34,17110.16
   457.2  753.29 1037.46 1304.89 1905.14  2956.7
River Rch & RM=15242,34, 16627.3
  471.67   777.3 1070.72 1346.86 1966.42  3038.8
River Rch & RM=15242,34,16144.43
  493.08  812.88 1120.04 1409.18  2057.4 3160.33
River Rch & RM=15242,34,15661.56
  514.01  847.67 1168.28 1470.13 2146.39 3278.48
River Rch & RM=15242,34, 15178.7
  558.52  921.75 1271.07 1600.07  2336.1 3528.41
River Rch & RM=15242,34,14695.83
  577.49  953.33  1314.9 1655.47 2416.99 3634.06
River Rch & RM=15242,34,14283.51
  590.07  974.26 1343.95 1692.19  2470.6 3703.83
River Rch & RM=15242,34,13871.18
  602.01  994.15 1371.58 1727.13 2521.62 3770.08
River Rch & RM=15242,34,13458.85
 1251.39 2072.37 2866.27 3613.37 5275.52 7118.37
River Rch & RM=15242,34,13046.53
 1266.62 2097.86 2901.79 3658.38 5341.24 7195.37
River Rch & RM=15242,34, 12634.2
  1324.4 2194.54 3036.53 3829.15 5590.57 7486.43
River Rch & RM=15242,34,12354.69
 1327.82 2200.26  3044.5 3839.27 5605.33 7503.61
River Rch & RM=15242,34, 12212.7
 1338.07 2217.42 3068.41 3869.58 5649.58 7555.07
River Rch & RM=15242,34,11889.34
 1487.59 2467.37 3416.57 4310.55  6293.4 8295.94
River Rch & RM=15242,34,11641.05
 1503.35 2493.77 3453.39 4357.24 6361.57 8373.96
River Rch & RM=15242,34,11431.06
 1506.45 2498.96 3460.64 4366.43 6374.99 8389.31
River Rch & RM=15242,34,11322.29
 1509.33 2503.79 3467.36 4374.96 6387.44 8403.55
River Rch & RM=15242,34,11144.48
 1514.19 2511.94 3478.74 4389.39 6408.51 8427.63
River Rch & RM=15242,34,10647.91
 1635.29 2714.76 3761.63 4748.07 6932.18 9022.31
River Rch & RM=15242,34,10394.28
 1665.82 2765.97 3833.13  4838.8 7064.65 9172.01
River Rch & RM=15242,34,10249.56
 1688.56 2804.08 3886.29 4906.23  7163.1 9282.86
River Rch & RM=15242,34,9828.013
 1735.13 2882.22 3995.43 5044.76 7365.35 9510.33
River Rch & RM=15242,34, 9406.47
 1759.69 2923.44    4053 5117.84 7472.05 9630.02
River Rch & RM=15242,34,9259.631
 1761.39  2926.3    4057 5122.91 7479.45 9638.32
River Rch & RM=15242,34,8661.608
 1785.21 2966.29 4112.87 5193.85 7583.02 9754.28
River Rch & RM=15242,34, 8266.31
 1791.96 2977.64 4128.74 5214.03 7612.48 9787.32
River Rch & RM=15242,34,7871.011
 1858.87 3090.12 4286.03 5413.88 7904.2610113.25
River Rch & RM=15242,34,7080.415
 1878.08 3122.45 4331.26 5471.36 7988.1910206.78
River Rch & RM=15242,34,6875.811
 1879.75 3125.26 4335.18 5476.35 7995.4710214.89
River Rch & RM=15242,34,6387.948
 1895.76 3152.21 4372.91 5524.32  8065.510292.89
River Rch & RM=15242,34,6298.868
 1910.71 3177.37 4408.12  5569.1 8130.8810365.61
River Rch & RM=15242,34,5867.929
 1920.85 3194.45 4432.03 5599.51 8175.2810414.98
River Rch & RM=15242,34,5461.214
 1942.97  3231.7 4484.18 5665.83 8272.1110522.48
Boundary for River Rch & Prof#=15242,34,1
Up Type= 0
Dn Type= 2
Boundary for River Rch & Prof#=15242,34,2
Up Type= 0
Dn Type= 2
Boundary for River Rch & Prof#=15242,34,2
Up Type= 0
Dn Type= 2
Boundary for River Rch & Prof#=15242,34,2
Up Type= 0
Dn Type= 2
Boundary for River Rch & Prof#=15242,34,2
Up Type= 0
Dn Type= 2
Boundary for River Rch & Prof#=15242,34,2
Up Type= 0
Dn Type= 2

--- 15242_ras.g01 (geometry) ---

Geom Title=15242
Program Version=4.10

River Reach=15242,34
Reach XY= 30
741486.453869998857184.060160354741710.412203282857043.435160384
741791.141369969857243.955993697742171.349703312857298.643493727
742546.349703312857560.362243682743074.995536685857600.726827055
743271.610119939857822.080993697743724.735119939858720.518493727
744097.130953312858930.153910354744943.485119969859105.935160369
745466.922619998859036.924743742747090.695055127859291.545172334
747735.151786685859488.747660279748060.672619998859756.976827011
748590.620536655859962.705993712748781.182396829860365.913317889
749137.495536655860517.393493652749121.870536655860729.633077055
749792.443453312861034.320577025749981.245536655861402.810160354
750226.037203342861333.799743697750634.336346835861959.518683523
751000.815129042862118.796951294751396.951785356862437.121050104
751416.115700006863089.907208696751554.028335124863531.656472713
752528.511588752864401.523919925752830.276953906865026.709619448
752926.494590163865757.000362456 752752.71026969866599.625763252

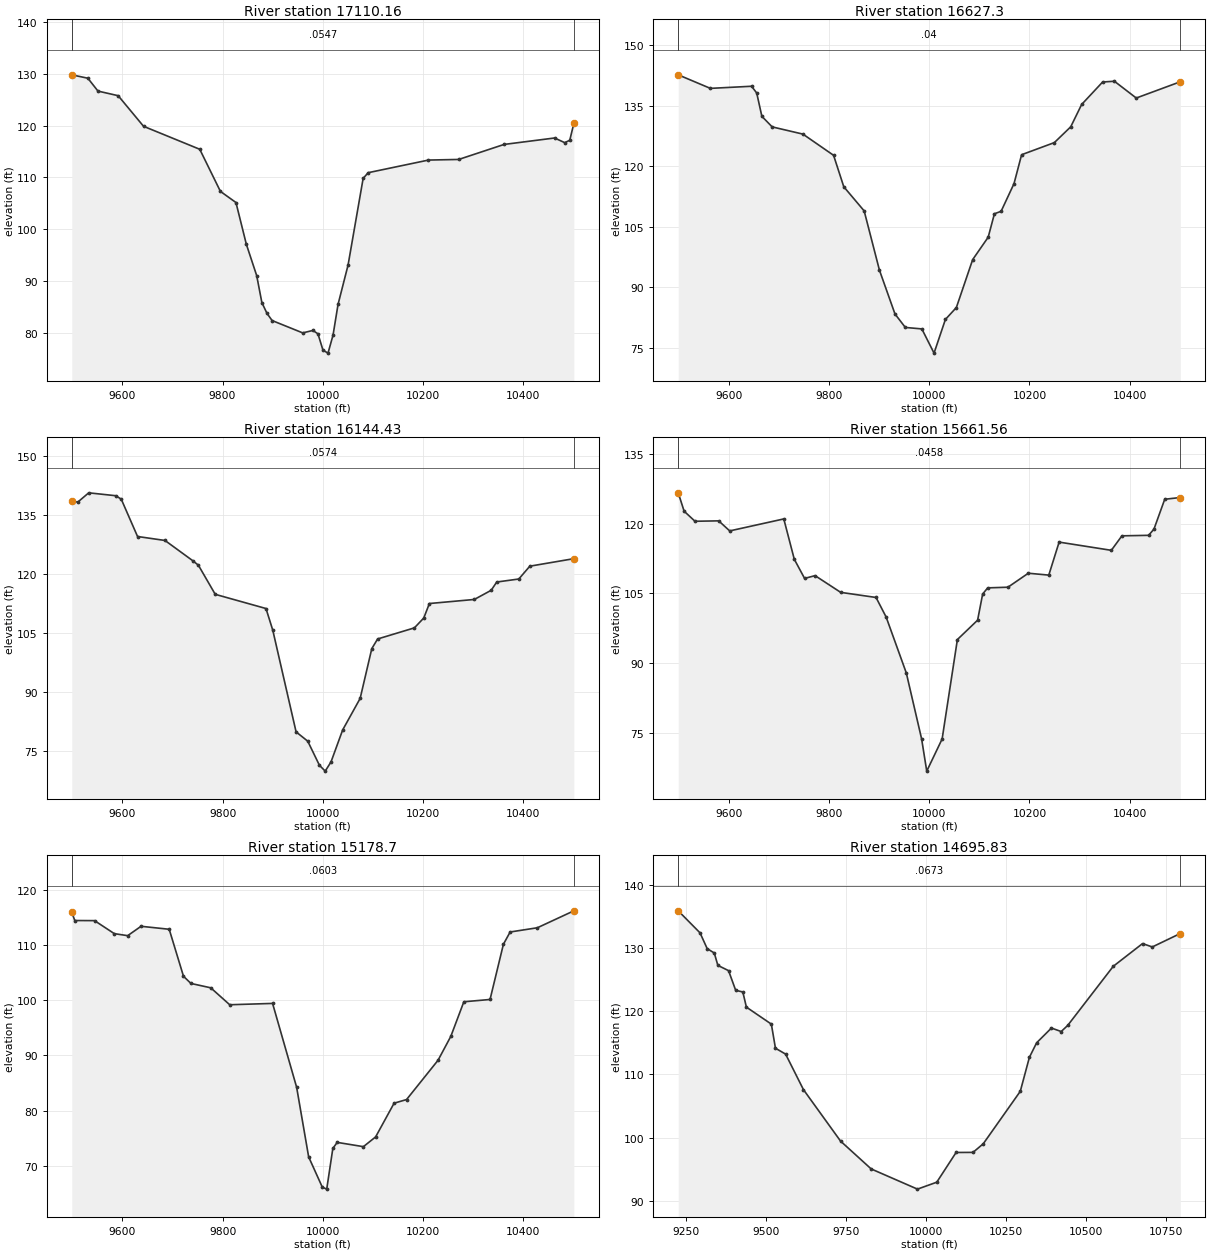
Type RM Length L Ch R = 1 ,17110.16,482.865700,482.865700,482.865700
XS GIS Cut Line= 6
741606.650721364857536.861663084741635.947412666857338.491276316
 741698.82076724857061.913583365   741696.804681856994.155613527
741705.103651162856866.935460563741741.748200763856546.899886004
#Sta/Elev= 30
9499.117129.78249531.233129.12689551.393126.64539591.713125.75559642.363119.8504
9754.512115.4151 9795.73107.28879826.747105.14119847.42597.097839868.10391.03959
9878.44285.836249888.69983.744269898.877 82.36779959.94779.985439980.30480.45833
9990.36179.8038110000.3876.6553210010.4376.0806710020.4679.5536110030.4685.49116
10050.46 93.075610080.53109.797910090.55110.8975 10210.9 113.335 10271.2113.4536
 10361.7 116.34910462.54117.594410482.71116.694310492.79117.153110500.96 120.407
#Mann= 3 , 0 , 0
9499.117  0.0547       09499.117  0.0547       010500.96  0.0547       0
#XS Ineff= 2 , 0
       0                               0
Bank Sta=9499.117,10500.96
Exp/Cntr=0.3,0.1

Type RM Length L Ch R = 1 , 16627.3,482.865700,482.865700,482.865700
XS GIS Cut Line= 6
741886.027075709857757.390440457741932.773579455857559.945556573
741971.392562705857362.096471248741984.283499714857312.848058795
 742024.03501755857240.015372933742206.577167791856814.329867711
#Sta/Elev= 30
9499.098142.69289563.213139.33489645.425139.85929655.701138.18339665.978132.4049
9686.531129.78589747.931127.99539809.088122.73969829.434114.94489870.125 108.956
9900.64394.251379931.60683.40699 9952.2880.069259985.21179.7052510009.5473.70248
10032.2382.0588810054.0885.0025410086.6396.8866810117.59102.440310130.03108.2503
10143.37108.859410169.14115.726110184.28122.8875 10249.6125.889710282.29129.8043
10304.09135.343310345.99 140.91710369.47141.101710413.06 136.94110500.97140.9721
#Mann= 3 , 0 , 0
9499.098    0.04       09499.098    0.04       010500.97    0.04       0
#XS Ineff= 2 , 0
       0                               0
Bank Sta=9499.098,10500.97
Exp/Cntr=0.3,0.1

Type RM Length L Ch R = 1 ,16144.43,482.865700,482.865700,482.865700
XS GIS Cut Line= 6
 742198.82417066 857926.28291187742251.603146598857798.793977764
742310.216980259857674.735739816742524.576709225857304.333205765
742587.186972383857180.631235818742654.131710316857035.208464878
#Sta/Elev= 30
9499.026138.50669511.238138.32889532.884140.66699586.999139.92889597.822139.0416
9630.291129.55969685.058128.55269740.525123.39939751.663122.26579785.332114.8543
9886.595111.24459900.146105.73899946.67879.872329969.94477.50592 9993.2171.38942
10004.7869.89188 10016.472.2421310039.6480.3694210074.5188.3834110097.75101.0406
10109.37103.498810182.76106.323910201.47108.8304 10212.7112.516110302.36113.5487
10335.99115.877410347.08117.983610391.12118.749510413.13122.012710500.97123.9235
#Mann= 3 , 0 , 0
9499.026  0.0574       09499.026  0.0574       010500.97  0.0574       0
#XS Ineff= 2 , 0
       0                               0
Bank Sta=9499.026,10500.97
Exp/Cntr=0.3,0.1

Type RM Length L Ch R = 1 ,15661.56,482.865700,482.865700,482.865700
XS GIS Cut Line= 6
742719.580208705858077.034109379742779.576145726857953.798225752
742817.768701232 857845.37837233742893.394272686857377.986781711
742924.339511312857263.628592963 742978.52300169857115.968738804
#Sta/Elev= 30
9499.084126.61439510.837122.66689532.523 120.5049579.801120.59419601.825118.4329
9709.701121.00739730.648112.3451  9751.2108.22959772.168108.8225 9823.27105.2294
 9893.79104.1324 9913.9299.93255 9954.1887.913429984.75373.732789994.96666.82212
10025.6873.7345810056.11 95.091110096.4699.2558810106.54104.877610116.63106.1954
10156.97106.335910197.64109.3413 10238.5108.935410259.11116.0261 10363.3114.2611
10384.42 117.37510437.68117.4827 10448.4118.826110469.83125.230410500.94125.6074
#Mann= 3 , 0 , 0
9499.084  0.0458       09499.084  0.0458       010500.94  0.0458       0
#XS Ineff= 2 , 0
       0                               0
Bank Sta=9499.084,10500.94
Exp/Cntr=0.3,0.1

Type RM Length L Ch R = 1 , 15178.7,482.865600,482.865600,482.865600
XS GIS Cut Line= 6
742874.118171009 858119.56837343742986.652988624857992.070309873
743062.872576686857920.536481986743411.867515275857675.045843843
743520.439850937857586.177120307743637.612537198857477.079492441
#Sta/Elev= 30
9499.051115.90469505.057114.39129544.494114.37249583.931112.01889610.608111.6508
9637.292113.3488 9693.49112.80879722.014104.30329736.837103.00739776.393102.2176
9814.248 99.15189899.77199.393619947.77984.221649971.78471.61943    999966.14971
10007.8465.7909710020.0273.1494510028.7274.2485710081.0273.4743410105.4275.23995
10142.2681.3400410167.1381.99699   1023089.1116910255.4793.4323510281.4699.68804
10333.75100.107210360.42110.098310373.85112.316310428.18113.082210500.98116.1464
#Mann= 3 , 0 , 0
9499.051  0.0603       09499.051  0.0603       010500.98  0.0603       0
#XS Ineff= 2 , 0
       0                 10135.5       0
Bank Sta=9499.051,10500.98
Exp/Cntr=0.3,0.1

Type RM Length L Ch R = 1 ,14695.83,412.326000,412.326000,412.326000
XS GIS Cut Line= 5
742743.877599686 858569.37991032743288.266718507858301.046266645
743533.434867769 858135.02689001743685.941039294857943.911561057
743763.159354031857528.863119438
#Sta/Elev= 30
9225.058 135.9199293.202132.4298  9315.5129.93529337.797129.23469348.946127.2782
9382.393126.4418 9404.69123.32389426.988123.06839438.137120.66529516.178117.9728
9529.004114.15489560.773113.22269616.517107.5968 9732.5799.441289828.34595.03246
9972.96691.8359110033.3592.9338710093.7497.6418610146.6297.6552210178.6899.02002
10294.43107.326610322.98112.7225 10345.6115.017610391.82117.352810422.33116.7993
10442.68117.765910585.08 127.12910676.62130.729910707.14130.197410794.75 132.327
#Mann= 3 , 0 , 0
9225.058  0.0673       09225.058  0.0673       010794.75  0.0673       0
#XS Ineff= 2 , 0
       09859.398        10115.55       0
Bank Sta=9225.058,10794.75
Exp/Cntr=0.3,0.1

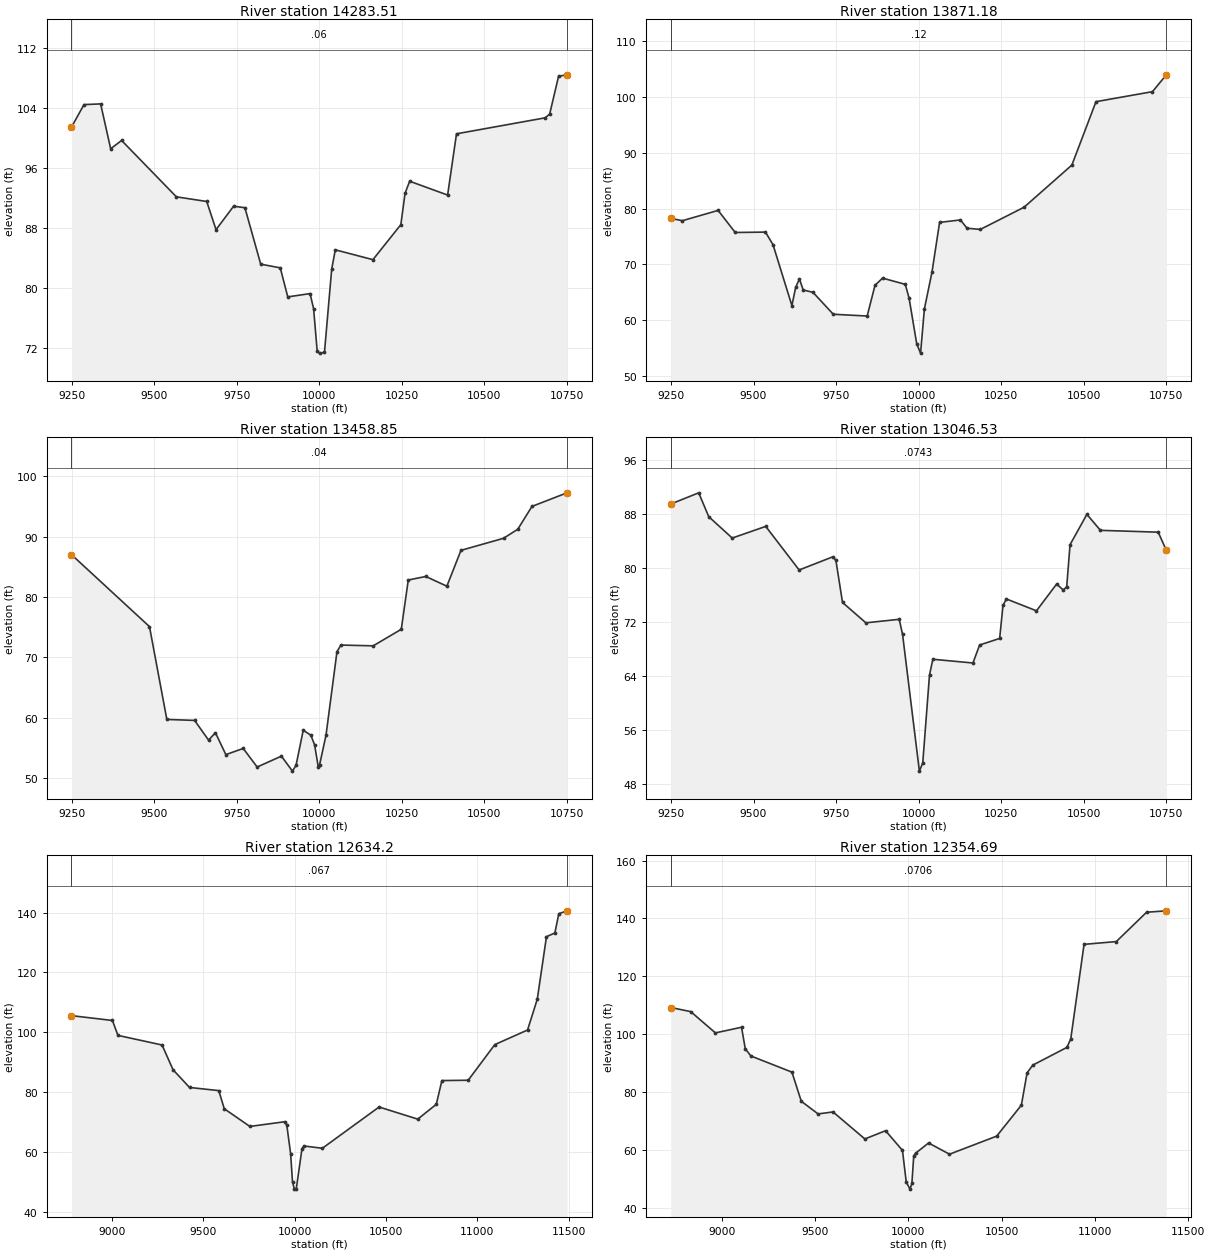
Type RM Length L Ch R = 1 ,14283.51,412.326000,412.326000,412.326000
XS GIS Cut Line= 6
743052.996672606859033.633620678743362.852505622858728.572011144
743517.709102537858620.293873521743846.209447246858440.690364664
744025.490889509858288.752874014744210.153405118 858096.04593768
#Sta/Elev= 30
9249.101 101.3959287.139 104.4019337.548104.49429367.965 98.52249401.11699.62561
9567.12192.122359659.07291.503089687.24687.751249740.50790.871359774.75490.67467
9822.72483.157439881.91982.666799904.66278.803179972.23979.237719982.95677.22791
9993.94971.53267   1000171.3133410015.8771.4018210037.7782.4813210048.7285.06662
 10162.783.7564810247.3588.4177610260.0592.5771810274.0294.1999410389.1192.35828
10416.02100.511310684.88102.641810698.37103.143510725.35108.180210750.92108.3655
#Mann= 3 , 0 , 0
9249.101    0.06       09249.101    0.06       010750.92    0.06       0
#XS Ineff= 2 , 0
       0                               0
Bank Sta=9249.101,10750.92
Exp/Cntr=0.3,0.1

Type RM Length L Ch R = 1 ,13871.18,412.325900,412.325900,412.325900
XS GIS Cut Line= 6
743555.124070117859485.727803032743894.102051198858877.672578021
744034.466272872858634.083583978744073.977715569858570.829704687
744128.811961476858488.082681312744328.910863607858199.921532327
#Sta/Elev= 30
 9249.0178.25059 9284.1977.827739392.51479.674359444.476 75.71989536.06775.79225
9558.965 73.5381 9616.2162.645019627.65965.916899638.95867.405279650.55765.43515
9680.032 65.02299741.64361.097059844.32860.781269868.08666.277039890.98467.56164
9959.84466.444769971.42463.964889994.584 55.790110006.1654.1469510017.6962.02582
10040.76  68.63210063.8277.5258110126.9677.9652410147.0476.4838910187.2176.26692
10319.8880.2396410464.7887.7810210537.8399.1155710709.06100.906710750.98103.9166
#Mann= 3 , 0 , 0
 9249.01    0.12       0 9249.01    0.12       010750.98    0.12       0
#XS Ineff= 2 , 0
       0 9922.43                       0
Bank Sta=9249.01,10750.98
Exp/Cntr=0.3,0.1

Type RM Length L Ch R = 1 ,13458.85,412.326000,412.326000,412.326000
XS GIS Cut Line= 6
744036.029404021859688.907290192 744238.48488037859085.589283927
 744264.09569822859026.318333534744337.131919238858888.546972027
744468.013453837858534.082878425744570.465633408858287.549832146
#Sta/Elev= 30
9249.054 87.03629485.55475.11351 9538.1759.744749622.35559.582229664.44856.33406
9685.49457.536799717.06453.91964 9769.6854.94223 9811.8451.867389885.45653.66773
9918.77951.187169929.67252.133259951.53557.959889974.46157.136629985.92455.55012
9997.38851.78977   1000152.2060510020.5457.1317310053.85 70.985210065.8472.05818
 10163.671.9301710248.6674.67121 10269.982.8277310323.0183.4126610386.8781.80322
10429.5987.7397310558.4989.7313910601.6391.2245710644.7995.0141510750.95  97.261
#Mann= 3 , 0 , 0
9249.054    0.04       09249.054    0.04       010750.95    0.04       0
#XS Ineff= 2 , 0
       09916.428                       0
Bank Sta=9249.054,10750.95
Exp/Cntr=0.3,0.1

Type RM Length L Ch R = 1 ,13046.53,412.326000,412.326000,412.326000
XS GIS Cut Line= 6
744565.234591974859808.363321249744610.309356616 859559.54716157
744676.721698592859121.379039323744747.169618905858708.648099492
744791.646589181 858491.63475573744832.614472605858331.229649396
#Sta/Elev= 30
9249.02789.488359333.74791.149119364.23587.612479435.37484.448689536.87586.17765
9638.13479.718719739.28581.653099749.39281.193119769.604 74.9091 9840.3571.89128
9941.41472.411649951.58170.1884410002.5949.9230310012.8151.1444910033.26 64.1827
10043.4866.4966810164.9165.9408110185.1468.6073810245.8769.5766810256.0174.47255
10266.1575.4284810357.43 73.671910418.5177.6341810438.8876.7477510449.0677.24019
10459.2583.4736210510.3187.9606510551.2585.5929110726.43 85.320610750.9782.63308
#Mann= 3 , 0 , 0
9249.027  0.0743       09249.027  0.0743       010750.97  0.0743       0
#XS Ineff= 2 , 0
       0                               0
Bank Sta=9249.027,10750.97
Exp/Cntr=0.3,0.1

Type RM Length L Ch R = 1 , 12634.2,279.510300,279.510300,279.510300
XS GIS Cut Line= 6
745062.087905355860316.726165235745139.021798273  859495.0216332
745060.351978438858901.914019878745066.610275139858576.531865348
745139.776589358858174.637415331 745315.95652476857653.157725296
#Sta/Elev= 30
8779.346 105.6029003.616103.98279033.83799.009619275.22695.807819335.38987.54039
9425.52981.63967 9585.6280.587589615.62574.540779755.77368.632479947.74670.21607
9957.95369.038119978.72859.55977 9989.1250.08178 9999.5247.7202810009.9147.91374
10041.0361.2518610051.2762.1191410152.4361.3512210462.9375.1205210674.3871.07209
10775.8776.0053410806.5583.9366810950.4484.0487511096.1395.9377511275.34100.8027
11328.55111.075411378.82131.933111424.84 133.19111446.32139.599611491.25140.5696
#Mann= 3 , 0 , 0
8779.346   0.067       08779.346   0.067       011491.25   0.067       0
#XS Ineff= 2 , 0
       0                               0
Bank Sta=8779.346,11491.25
Exp/Cntr=0.3,0.1

Type RM Length L Ch R = 1 ,12354.69,141.996000,141.996000,141.996000
XS GIS Cut Line= 6
745259.001486658860298.986202957 745302.51034984860119.994044289
745323.343683153859344.994044289745408.413127601858655.410710961
745521.954794258 858057.14682205745588.185303777857670.802183192
#Sta/Elev= 30
8727.369109.23458834.383107.81538966.587100.46389106.638102.41159126.64594.99983
9156.65692.489669376.73586.905299426.75376.843449516.786 72.47219596.81573.15564
9767.45363.825579878.28766.67116 9968.97 59.86559989.12148.9423910009.2746.48883
10019.3548.4431410029.4258.05052 10039.558.9011710108.7662.4331210220.8658.55387
10473.69 64.796810606.0175.4877610636.5486.6382310667.0889.3254610850.2995.46633
10870.65 98.4135 10941.9131.055711114.54132.012711276.87142.146111382.59 142.635
#Mann= 3 , 0 , 0
8727.369  0.0706       08727.369  0.0706       011382.59  0.0706       0
#XS Ineff= 2 , 0
       0                               0
Bank Sta=8727.369,11382.59
Exp/Cntr=0.3,0.1

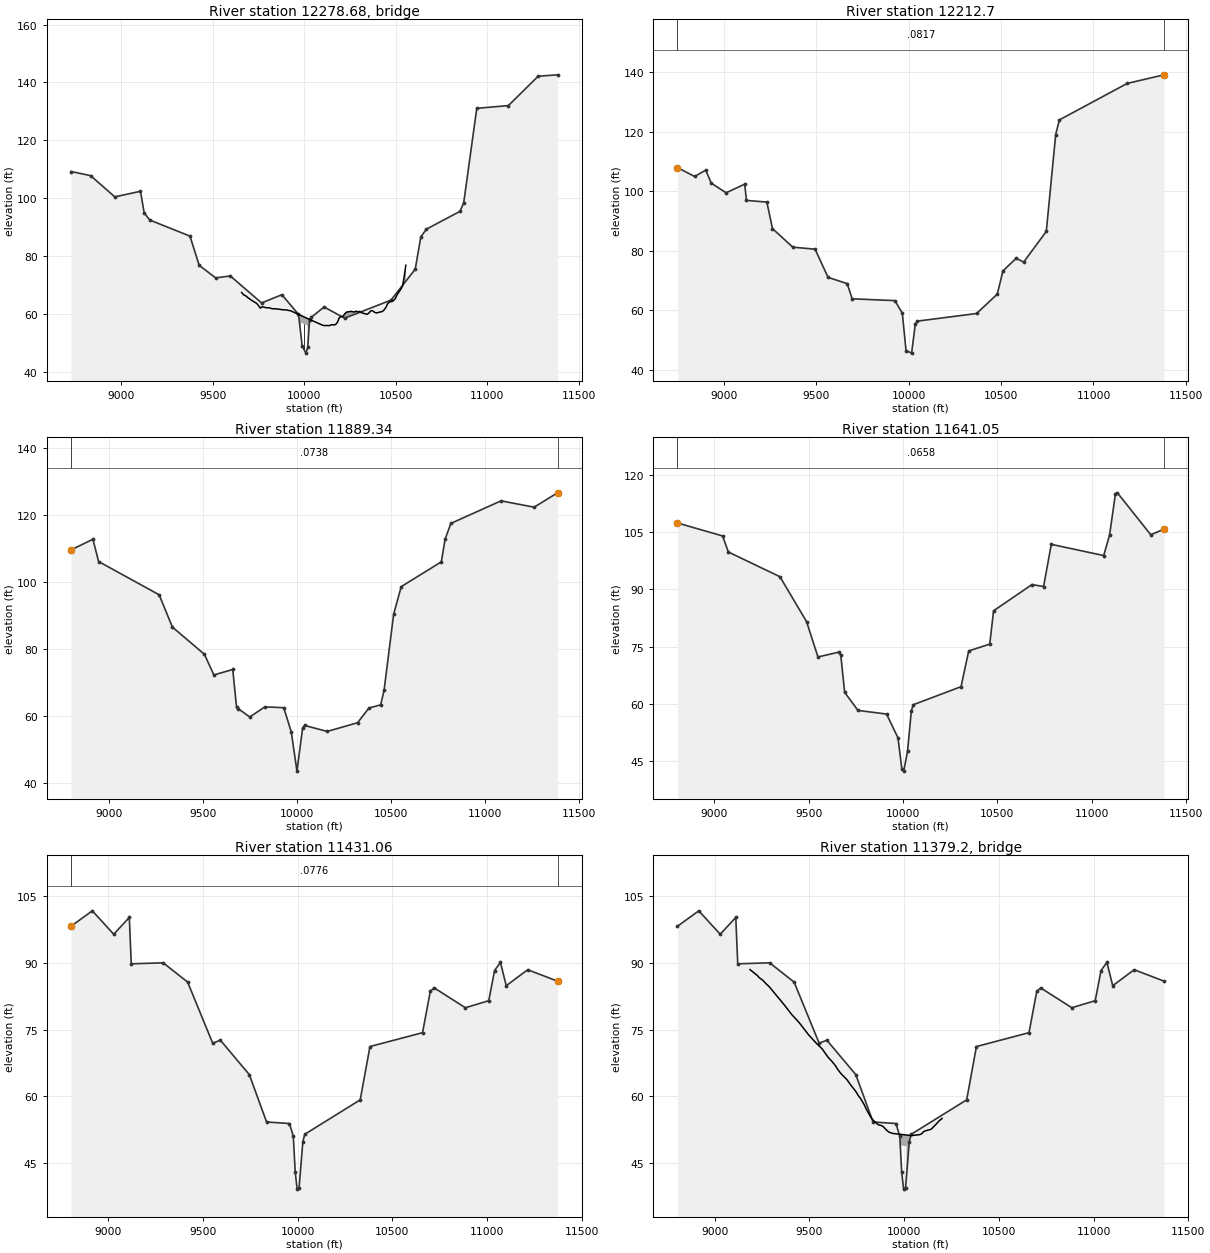
Type RM Length L Ch R = 3 ,12278.68,,,
BEGIN DESCRIPTION:
END DESCRIPTION:
Bridge Culvert--1,0,-1,-1, 0
Deck Dist Width WeirC Skew NumUp NumDn MinLoCord MaxHiCord MaxSubmerge Is_Ogee
43.603050,54.789900,2.6,0, 60, 60, , , 0.95, 0, 0,0,,
 9658.56 9670.31 9680.33 9690.36 9710.41 9740.49 9750.52 9760.54 9770.57 9790.62
 9810.67 9824.65 9850.78 9880.86 9900.91 9927.17 9981.30 9981.3010018.7010018.70
10101.4310111.4610121.4910131.5110141.5410151.5610161.5910171.6210181.6410191.72
10201.8910212.0510222.2110232.3810242.5410252.7010273.0310283.1910293.3510303.51
10313.6810344.1610354.3310364.4910374.6510384.8210394.9810415.3010425.4710435.63
10445.7910455.9510466.1210486.4410496.6010506.7710527.0910537.2610547.4210554.64
   67.45   66.58   66.32   65.77   64.84   63.68   62.91   62.03   62.52   62.21
   62.11   61.84   61.77   61.49   61.43   61.09   59.52   59.52   58.44   58.44
   56.10   55.99   56.05   55.96   56.08   56.33   56.24   56.38   57.17   58.76
   59.12   59.21   60.12   60.72   60.74   60.93   60.70   61.00   60.72   60.92
   60.42   59.88   60.42   61.17   61.07   60.56   60.35   60.72   60.83   61.38
   62.26   63.60   64.19   64.59   65.26   66.64   68.52   69.75   73.56   76.84
 -932.55 -933.42 -933.68 -934.23 -935.16 -936.32 -937.09 -937.97 -937.48 -937.79
 -937.89 -938.16 -938.23 -938.51 -938.57 -938.91 -940.48   57.02   55.94 -941.56
 -943.90 -944.01 -943.95 -944.04 -943.92 -943.67 -943.76 -943.62 -942.83 -941.24
 -940.88 -940.79 -939.88 -939.28 -939.26 -939.07 -939.30 -939.00 -939.28 -939.08
 -939.58 -940.12 -939.58 -938.83 -938.93 -939.44 -939.65 -939.28 -939.17 -938.62
 -937.74 -936.40 -935.81 -935.41 -934.74 -933.36 -931.48 -930.25 -926.44 -923.16
 9658.56 9670.31 9680.33 9690.36 9710.41 9740.49 9750.52 9760.54 9770.57 9790.62
 9810.67 9824.65 9850.78 9880.86 9900.91 9927.17 9981.30 9981.3010018.7010018.70
10101.4310111.4610121.4910131.5110141.5410151.5610161.5910171.6210181.6410191.72
10201.8910212.0510222.2110232.3810242.5410252.7010273.0310283.1910293.3510303.51
10313.6810344.1610354.3310364.4910374.6510384.8210394.9810415.3010425.4710435.63
10445.7910455.9510466.1210486.4410496.6010506.7710527.0910537.2610547.4210554.64
   67.45   66.58   66.32   65.77   64.84   63.68   62.91   62.03   62.52   62.21
   62.11   61.84   61.77   61.49   61.43   61.09   59.52   59.52   58.44   58.44
   56.10   55.99   56.05   55.96   56.08   56.33   56.24   56.38   57.17   58.76
   59.12   59.21   60.12   60.72   60.74   60.93   60.70   61.00   60.72   60.92
   60.42   59.88   60.42   61.17   61.07   60.56   60.35   60.72   60.83   61.38
   62.26   63.60   64.19   64.59   65.26   66.64   68.52   69.75   73.56   76.84
 -932.55 -933.42 -933.68 -934.23 -935.16 -936.32 -937.09 -937.97 -937.48 -937.79
 -937.89 -938.16 -938.23 -938.51 -938.57 -938.91 -940.48   57.02   55.94 -941.56
 -943.90 -944.01 -943.95 -944.04 -943.92 -943.67 -943.76 -943.62 -942.83 -941.24
 -940.88 -940.79 -939.88 -939.28 -939.26 -939.07 -939.30 -939.00 -939.28 -939.08
 -939.58 -940.12 -939.58 -938.83 -938.93 -939.44 -939.65 -939.28 -939.17 -938.62
 -937.74 -936.40 -935.81 -935.41 -934.74 -933.36 -931.48 -930.25 -926.44 -923.16
Pier Skew, UpSta & Num, DnSta & Num=  ,10000.00, 2 ,10000.00, 2 , 0 , 0 , 0 ,,
    2.00    2.00
 -941.02   58.98
    2.00    2.00
 -941.02   58.98
BR Coef=-1 , 0 , 0 ,, 0 ,,,0.8,0,1,0,
WSPro=,,,, 1 ,,,, 0 ,,,, 0 ,,,,-1 ,-1 ,-1 , 0 , 0 , 0 , 0 , 0
BC Design=,, 0 ,, 0 ,,,,,,

Type RM Length L Ch R = 1 , 12212.7,323.355200,323.355200,323.355200
XS GIS Cut Line= 5
745396.503455466  860286.5986382745404.246460915860255.063488737
745470.913127661859371.730155408745540.357572079858665.132933185
 745734.44063359857680.281695307
#Sta/Elev= 30
8749.409108.04018842.115105.03088902.286107.17048932.371102.78929012.59999.54287
9112.883102.45419122.91196.985839233.224  96.425 9263.3187.523989373.62281.26668
9493.96480.599749564.16371.126189667.726 69.02349694.58563.915529925.69363.31403
9965.886 59.10759985.98246.5376410016.1345.6623810036.2255.4489810046.2756.40553
10367.8158.9834410479.79 65.501410510.3673.2970910581.7177.5335610622.4876.26254
10744.7986.5654510795.75119.1393 10815.5124.049911183.06136.323211381.52139.1995
#Mann= 3 , 0 , 0
8749.409  0.0817       08749.409  0.0817       011381.52  0.0817       0
#XS Ineff= 2 , 0
       0                               0
Bank Sta=8749.409,11381.52
Exp/Cntr=0.3,0.1

Type RM Length L Ch R = 1 ,11889.34,248.287100,248.287100,248.287100
XS GIS Cut Line= 6
745679.866316842860280.232960374745730.533698585859935.998958839
745827.889616192859043.449679665745883.563296735858651.511941211
745976.090505919858162.819423191746096.097527549857725.801314072
#Sta/Elev= 30
8795.689109.58628912.482112.76188942.824106.12199265.49696.208659335.91186.59019
9506.82978.46849  9557.1 72.3139 9657.6473.953239677.74862.772389687.80262.23142
9748.17259.78357 9828.6862.797419929.31562.564049969.56955.306699999.758 43.6517
10029.9256.4825810039.9757.2764710161.0255.4809110322.6858.0742910383.3362.46584
10446.1263.4056610464.2967.8692510514.9890.4338910555.5498.6517510768.98106.0241
10789.43112.834810820.12117.493711087.23124.212311263.54122.3201 11388.2126.6006
#Mann= 3 , 0 , 0
8795.689  0.0738       08795.689  0.0738       0 11388.2  0.0738       0
#XS Ineff= 2 , 0
       0                               0
Bank Sta=8795.689,11388.2
Exp/Cntr=0.3,0.1

Type RM Length L Ch R = 1 ,11641.05,209.996900,209.996900,209.996900
XS GIS Cut Line= 6
745895.644397834860300.661654428745952.601483526859967.149012556
746053.433500274859223.414295092746153.244860824858599.186694814
746256.530380039858120.912147313746357.229353333857768.242261638
#Sta/Elev= 30
8804.978 107.431 9044.15104.0209 9074.5699.816549347.55993.336569488.79481.56841
9549.31872.272699660.27973.550319670.36672.68541 9690.5463.007749761.15258.25142
9912.51757.297799973.22451.051659993.45942.9329410003.5842.3206310023.8247.55792
10044.0758.1313110054.19 59.745910307.2464.4793310347.7373.8570410459.2575.64642
10479.5584.39639 10683.191.2686610744.4190.7501510785.32101.826911063.0298.88084
 11094.1104.283311125.19 115.12811135.55115.341111312.35104.330811382.26105.8023
#Mann= 3 , 0 , 0
8804.978  0.0658       08804.978  0.0658       011382.26  0.0658       0
#XS Ineff= 2 , 0
       0                               0
Bank Sta=8804.978,11382.26
Exp/Cntr=0.3,0.1

Type RM Length L Ch R = 1 ,11431.06,108.766000,108.766000,108.766000
XS GIS Cut Line= 5
746041.659516751860314.485571009746174.142294258859760.896822065
746250.531183183859352.910710946746318.239516497858830.341266513
746563.703376844857801.799845741
#Sta/Elev= 30
8803.35998.283498915.937101.75639029.04396.485579111.302100.26759121.584 89.8284
9290.33490.049079419.27585.703959551.53471.950959592.22972.622559744.83564.88595
9835.96754.21914 9956.9753.872599977.13750.995569987.22142.957279997.305  39.102
10007.3939.3317210027.5649.8147510037.6451.4505910330.3759.2059410381.7771.20362
10659.3574.3244110700.4883.6583610721.0484.4067410885.5379.93976 11008.981.52462
11039.74 88.317611070.5990.1534811101.4384.9022811214.5288.4973611372.0285.92745
#Mann= 3 , 0 , 0
8803.359  0.0776       08803.359  0.0776       011372.02  0.0776       0
#XS Ineff= 2 , 0
       0                               0
Bank Sta=8803.359,11372.02
Exp/Cntr=0.3,0.1

Type RM Length L Ch R = 3 , 11379.2,,,
BEGIN DESCRIPTION:
END DESCRIPTION:
Bridge Culvert--1,0,-1,-1, 0
Deck Dist Width WeirC Skew NumUp NumDn MinLoCord MaxHiCord MaxSubmerge Is_Ogee
26.883000,55.000000,2.6,0, 49, 49, , , 0.95, 0, 0,0,,
 9186.28 9225.24 9235.29 9255.38 9275.48 9285.53 9365.93 9406.13 9446.32 9496.57
 9536.81 9567.05 9597.30 9617.46 9637.62 9647.70 9657.78 9667.86 9698.10 9720.77
 9738.42 9748.50 9758.58 9768.66 9788.82 9800.15 9819.06 9829.14 9839.22 9859.38
 9869.46 9879.54 9889.62 9909.79 9919.87 9940.03 9982.26 9982.2610012.2610012.26
10037.9210081.4010091.5710101.7510111.9310142.4510172.9810183.1510200.41
   88.53   87.19   86.71   86.07   85.15   84.79   80.66   78.44   76.57   73.80
   71.93   70.69   68.86   67.93   66.89   66.17   65.59   65.05   63.75   62.39
   61.45   60.85   60.12   59.58   58.16   57.13   55.66   55.01   54.52   53.73
   53.50   53.43   53.17   52.28   51.94   51.64   51.43   51.43   51.28   51.28
   51.15   51.36   51.52   52.00   52.22   52.57   53.90   54.41   55.01
 -911.47 -912.81 -913.29 -913.93 -914.85 -915.21 -919.34 -921.56 -923.43 -926.20
 -928.07 -929.31 -931.14 -932.07 -933.11 -933.83 -934.41 -934.95 -936.25 -937.61
 -938.55 -939.15 -939.88 -940.42 -941.84 -942.87 -944.34 -944.99 -945.48 -946.27
 -946.50 -946.57 -946.83 -947.72 -948.06 -948.36 -948.57   48.93   48.78 -948.72
 -948.85 -948.64 -948.48 -948.00 -947.78 -947.43 -946.10 -945.59 -944.99
 9186.28 9225.24 9235.29 9255.38 9275.48 9285.53 9365.93 9406.13 9446.32 9496.57
 9536.81 9567.05 9597.30 9617.46 9637.62 9647.70 9657.78 9667.86 9698.10 9720.77
 9738.42 9748.50 9758.58 9768.66 9788.82 9800.15 9819.06 9829.14 9839.22 9859.38
 9869.46 9879.54 9889.62 9909.79 9919.87 9940.03 9984.36 9984.3610014.3610014.36
10037.9210081.4010091.5710101.7510111.9310142.4510172.9810183.1510200.41
   88.53   87.19   86.71   86.07   85.15   84.79   80.66   78.44   76.57   73.80
   71.93   70.69   68.86   67.93   66.89   66.17   65.59   65.05   63.75   62.39
   61.45   60.85   60.12   59.58   58.16   57.13   55.66   55.01   54.52   53.73
   53.50   53.43   53.17   52.28   51.94   51.64   51.42   51.42   51.27   51.27
   51.15   51.36   51.52   52.00   52.22   52.57   53.90   54.41   55.01
 -911.47 -912.81 -913.29 -913.93 -914.85 -915.21 -919.34 -921.56 -923.43 -926.20
 -928.07 -929.31 -931.14 -932.07 -933.11 -933.83 -934.41 -934.95 -936.25 -937.61
 -938.55 -939.15 -939.88 -940.42 -941.84 -942.87 -944.34 -944.99 -945.48 -946.27
 -946.50 -946.57 -946.83 -947.72 -948.06 -948.36 -948.58   48.92   48.77 -948.73
 -948.85 -948.64 -948.48 -948.00 -947.78 -947.43 -946.10 -945.59 -944.99
BR Coef=-1 , 0 , 0 ,, 0 ,,,0.8,0,1,0,
WSPro=,,,, 1 ,,,, 0 ,,,, 0 ,,,,-1 ,-1 ,-1 , 0 , 0 , 0 , 0 , 0
BC Design=,, 0 ,, 0 ,,,,,,

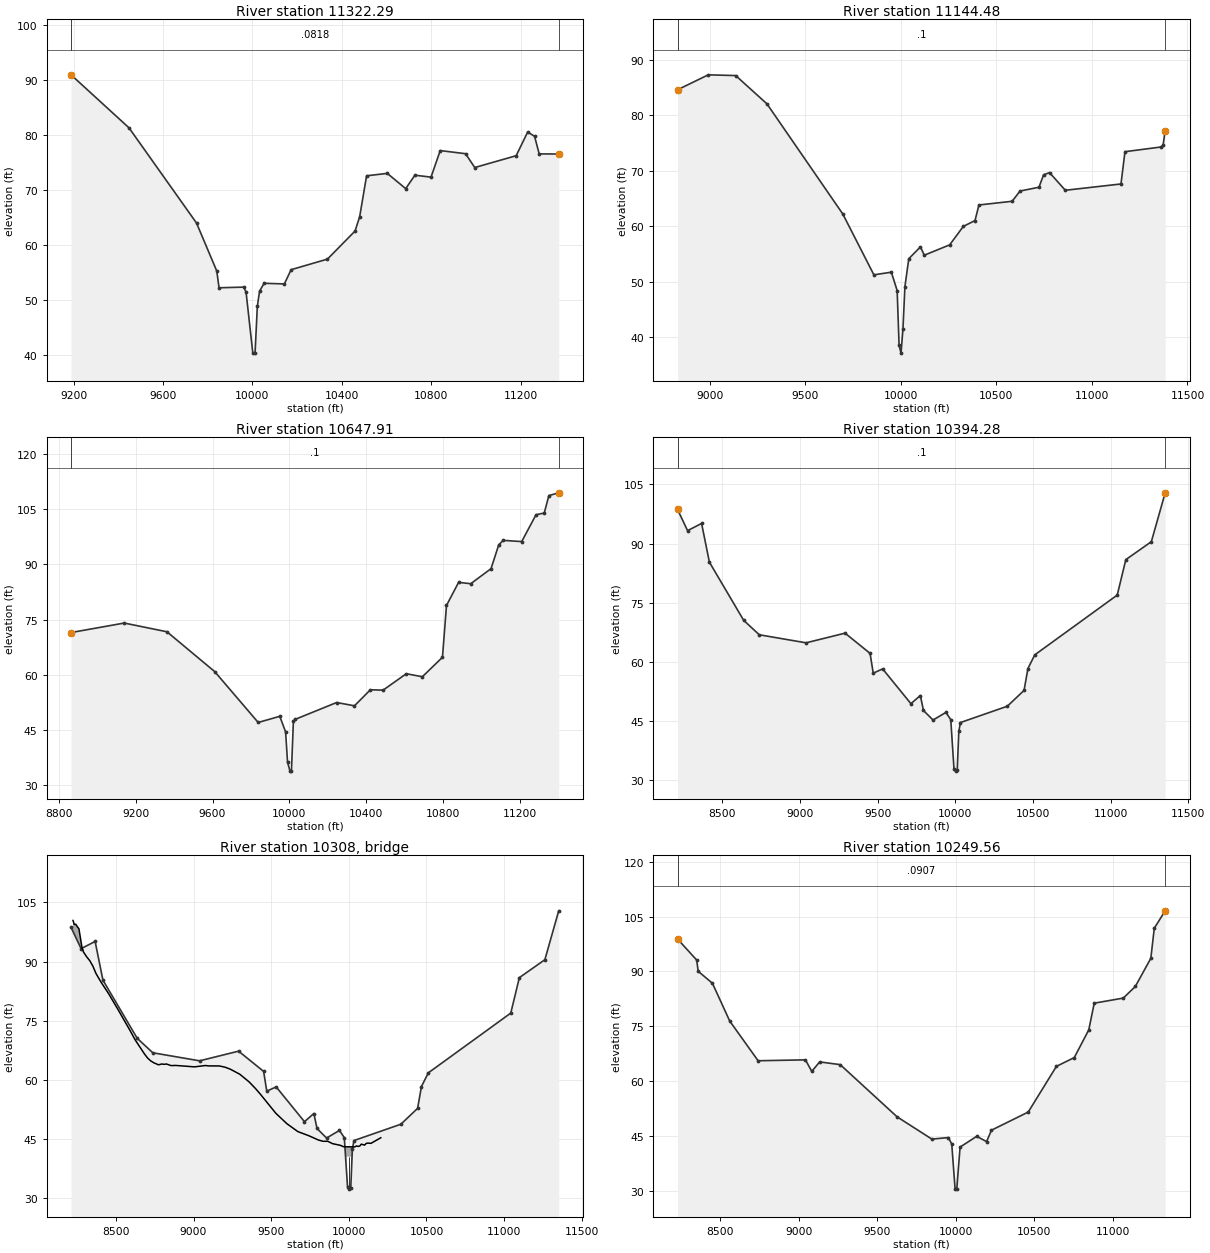
Type RM Length L Ch R = 1 ,11322.29,177.811500,177.811500,177.811500
XS GIS Cut Line= 5
746294.010774791859963.091157183746337.336738735859537.632933185
746418.586738735858888.674599841746674.142294258857845.966266498
746684.353500676857821.408737013
#Sta/Elev= 30
9188.89391.013959448.319 81.3524 9750.2264.021249840.92255.27019    985152.22552
9961.85952.346119971.93751.4330110002.1740.3223210012.2540.4073510022.3348.83968
10032.4151.6144910052.5653.0433310143.2652.92728 10173.555.5206510336.14 57.4499
10459.6962.5667510480.2865.1806510511.1772.6226610603.8373.06182 10686.270.28421
10727.3872.7335710799.4572.3782110840.6477.2149210953.89 76.647810995.0874.12843
 11180.476.2820111231.8880.5905311262.7779.8157211283.3676.6140111370.7476.58741
#Mann= 3 , 0 , 0
9188.893  0.0818       09188.893  0.0818       011370.74  0.0818       0
#XS Ineff= 2 , 0
       0                               0
Bank Sta=9188.893,11370.74
Exp/Cntr=0.3,0.1

Type RM Length L Ch R = 1 ,11144.48,496.574300,496.574300,496.574300
XS GIS Cut Line= 6
746329.377242923860341.725119043746429.650382257859892.689991617
746571.968976406859109.542129391746669.594763551858637.644736445
746749.649870656858314.191246198746889.478395905857854.747051471
#Sta/Elev= 30
8831.72384.633138992.75487.329499136.15587.194489299.68282.092479696.561 62.2188
9859.21351.244769950.54251.722979980.95248.403449991.08838.5016710001.2237.11864
10011.3541.4962310021.4949.1001510041.7754.14995 10102.756.28569 10123.154.78476
10255.7256.6537710327.1359.9818210388.3461.0427710408.7463.8482110582.7664.51463
10623.8866.3649510722.8367.0459610747.2269.2888810778.1969.6903210860.8466.50102
11152.0667.6368811173.0173.4623211361.9574.31026 11372.574.6687211383.3277.27464
#Mann= 3 , 0 , 0
8831.723     0.1       08831.723     0.1       011383.32     0.1       0
#XS Ineff= 2 , 0
       0                               0
Bank Sta=8831.723,11383.32
Exp/Cntr=0.3,0.1

Type RM Length L Ch R = 1 ,10647.91,253.623500,253.623500,253.623500
XS GIS Cut Line= 6
746750.751973568860381.618584658746938.115275739859757.213002347
747069.717943508859147.847646943747174.433591141 858740.81984241
747326.472433561858260.695751782747443.350597703857944.766186463
#Sta/Elev= 30
8863.983 71.50539140.49574.081849362.80371.716449611.20160.910139837.48347.10316
 9949.73 48.77219980.083 44.52759990.20136.2847410002.98 33.896710010.4434.04717
10020.5747.4161710030.69 47.964110245.4452.5145810338.2851.6250510420.91  55.966
10487.2655.87783 10607.960.3312510691.34 59.509210795.9664.7940410816.9478.85268
10879.8885.1245810943.1684.76164 11048.788.8466711088.8495.33672 11112.496.52082
11208.1296.19253 11282.6103.475511325.44 103.94211349.43108.674211400.67109.4244
#Mann= 3 , 0 , 0
8863.983     0.1       08863.983     0.1       011400.67     0.1       0
#XS Ineff= 2 , 0
       0                               0
Bank Sta=8863.983,11400.67
Exp/Cntr=0.3,0.1

Type RM Length L Ch R = 1 ,10394.28,144.726200,144.726200,144.726200
XS GIS Cut Line= 5
 747068.10017395861129.399078041747173.187433153859972.181544289
 747239.85409984859526.348210946747373.187433153859047.181544289
 747813.06892662858115.900904994
#Sta/Elev= 30
  8211.598.673018276.16493.271798366.53495.10158 8416.7485.274528637.64570.49597
8738.05766.836719039.29164.79319 9290.3267.248489451.51962.108599471.74157.08981
9532.40858.169539714.40949.342449775.07651.417649795.29947.611349856.80845.19174
9939.848 47.12579970.98845.283659991.74732.8071710002.1332.2178110012.51 32.4064
10022.8942.3370910033.2744.5531210335.1148.6937710442.9552.7190510467.83 58.2735
10512.0661.7412211042.91 76.915211098.2185.9172911262.4590.4637911351.58102.8747
#Mann= 3 , 0 , 0
  8211.5     0.1       0  8211.5     0.1       011351.58     0.1       0
#XS Ineff= 2 , 0
       0                               0
Bank Sta=8211.5,11351.58
Exp/Cntr=0.3,0.1

Type RM Length L Ch R = 3 ,   10308,,,
BEGIN DESCRIPTION:
END DESCRIPTION:
Bridge Culvert--1,0,-1,-1, 0
Deck Dist Width WeirC Skew NumUp NumDn MinLoCord MaxHiCord MaxSubmerge Is_Ogee
51.201750,42.322700,2.6,0, 60, 60, , , 0.95, 0, 0,0,,
 8224.21 8232.11 8242.13 8252.16 8262.18 8282.23 8292.26 8312.31 8332.36 8352.41
 8372.46 8405.09 8452.78 8513.13 8593.60 8623.77 8684.12 8704.24 8724.36 8744.47
 8774.65 8794.79 8814.93 8825.00 8855.21 8885.42 9006.26 9076.75 9096.89 9167.37
 9205.20 9237.86 9298.28 9358.70 9398.98 9429.31 9530.45 9601.26 9672.06 9742.86
 9803.55 9833.88 9864.19 9894.75 9946.40 9965.22 9984.58 9984.5810015.4210015.42
10037.7810049.7110060.0510070.3810080.7110101.3710111.7010122.0310142.7010205.96
  100.43   99.41   99.46   98.82   98.34   93.47   92.37   91.19   90.20   88.80
   86.93   84.74   81.88   77.87   72.33   70.14   66.54   65.51   64.78   64.29
   63.78   63.98   63.90   64.00   63.58   63.62   63.26   63.60   63.50   63.49
   63.15   62.65   61.38   59.42   57.76   56.38   51.46   48.83   46.82   45.77
   44.70   44.36   44.37   43.77   43.33   42.99   42.98   42.98   42.95   42.95
   42.93   43.18   43.06   43.16   43.64   43.39   43.81   43.91   43.84   45.26
 -899.57 -900.59 -900.54 -901.18 -901.66 -906.53 -907.63 -908.81 -909.80 -911.20
 -913.07 -915.26 -918.12 -922.13 -927.67 -929.86 -933.46 -934.49 -935.22 -935.71
 -936.22 -936.02 -936.10 -936.00 -936.42 -936.38 -936.74 -936.40 -936.50 -936.51
 -936.85 -937.35 -938.62 -940.58 -942.24 -943.62 -948.54 -951.17 -953.18 -954.23
 -955.30 -955.64 -955.63 -956.23 -956.67 -957.01 -957.02   40.48   40.45 -957.05
 -957.07 -956.82 -956.94 -956.84 -956.36 -956.61 -956.19 -956.09 -956.16 -954.74
 8224.21 8232.11 8242.13 8252.16 8262.18 8282.23 8292.26 8312.31 8332.36 8352.41
 8372.46 8405.09 8452.78 8513.13 8593.60 8623.77 8684.12 8704.24 8724.36 8744.47
 8774.65 8794.79 8814.93 8825.00 8855.21 8885.42 9006.26 9076.75 9096.89 9167.37
 9205.20 9237.86 9298.28 9358.70 9398.98 9429.31 9530.45 9601.26 9672.06 9742.86
 9803.55 9833.88 9864.19 9894.75 9946.40 9965.22 9984.58 9984.5810015.4210015.42
10037.7810049.7110060.0510070.3810080.7110101.3710111.7010122.0310142.7010205.96
  100.43   99.41   99.46   98.82   98.34   93.47   92.37   91.19   90.20   88.80
   86.93   84.74   81.88   77.87   72.33   70.14   66.54   65.51   64.78   64.29
   63.78   63.98   63.90   64.00   63.58   63.62   63.26   63.60   63.50   63.49
   63.15   62.65   61.38   59.42   57.76   56.38   51.46   48.83   46.82   45.77
   44.70   44.36   44.37   43.77   43.33   42.99   42.98   42.98   42.95   42.95
   42.93   43.18   43.06   43.16   43.64   43.39   43.81   43.91   43.84   45.26
 -899.57 -900.59 -900.54 -901.18 -901.66 -906.53 -907.63 -908.81 -909.80 -911.20
 -913.07 -915.26 -918.12 -922.13 -927.67 -929.86 -933.46 -934.49 -935.22 -935.71
 -936.22 -936.02 -936.10 -936.00 -936.42 -936.38 -936.74 -936.40 -936.50 -936.51
 -936.85 -937.35 -938.62 -940.58 -942.24 -943.62 -948.54 -951.17 -953.18 -954.23
 -955.30 -955.64 -955.63 -956.23 -956.67 -957.01 -957.02   40.48   40.45 -957.05
 -957.07 -956.82 -956.94 -956.84 -956.36 -956.61 -956.19 -956.09 -956.16 -954.74
Pier Skew, UpSta & Num, DnSta & Num=  ,10000.00, 2 ,10000.00, 2 , 0 , 0 , 0 ,,
    2.00    2.00
 -957.04   42.96
    2.00    2.00
 -957.04   42.96
BR Coef=-1 , 0 , 0 ,, 0 ,,,0.8,0,1,0,
WSPro=,,,, 1 ,,,, 0 ,,,, 0 ,,,,-1 ,-1 ,-1 , 0 , 0 , 0 , 0 , 0
BC Design=,, 0 ,, 0 ,,,,,,

Type RM Length L Ch R = 1 ,10249.56,421.543000,421.543000,421.543000
XS GIS Cut Line= 6
  747209.6842843861156.367480025747272.610555559860448.446928322
747377.562433153859534.334322065747507.562433153 859146.83432205
747818.952226418858609.402920212747998.460530158858201.714718941
#Sta/Elev= 30
8226.87698.870128348.72293.128858358.76290.034478449.11686.76765 8559.5576.42061
 8740.2665.567059041.71465.811149081.97762.662879132.30665.24645 9263.1664.50356
9625.52550.22571 9846.9744.132669952.485 44.55079973.70442.767599994.923 30.5113
10005.5330.4488510026.7541.9522310132.8544.8948710195.4843.4458210226.7646.57051
10460.9151.5316310640.4464.0343710754.0866.4309810846.5474.0105810881.2181.31459
11066.5682.7087411142.9985.8835611241.76 93.590311263.71101.809511333.16106.5759
#Mann= 3 , 0 , 0
8226.876  0.0907       08226.876  0.0907       011333.16  0.0907       0
#XS Ineff= 2 , 0
       0                               0
Bank Sta=8226.876,11333.16
Exp/Cntr=0.3,0.1