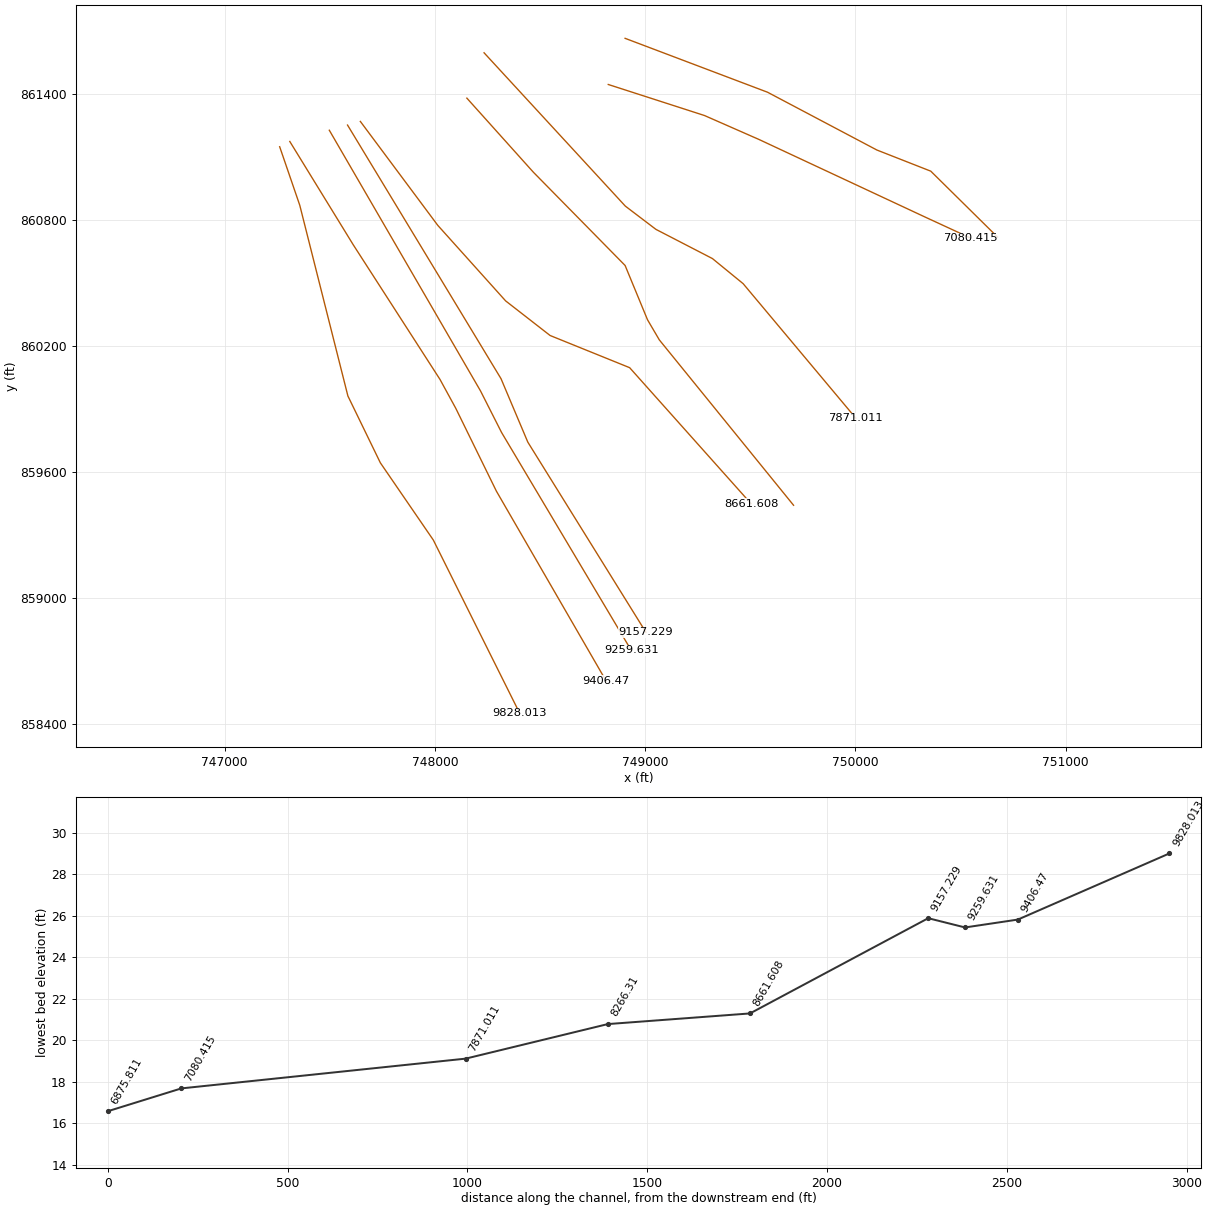
HEC-RAS study 15242_ras.prj: 15242

--- 15242_ras.g01 (geometry) --- (continued)

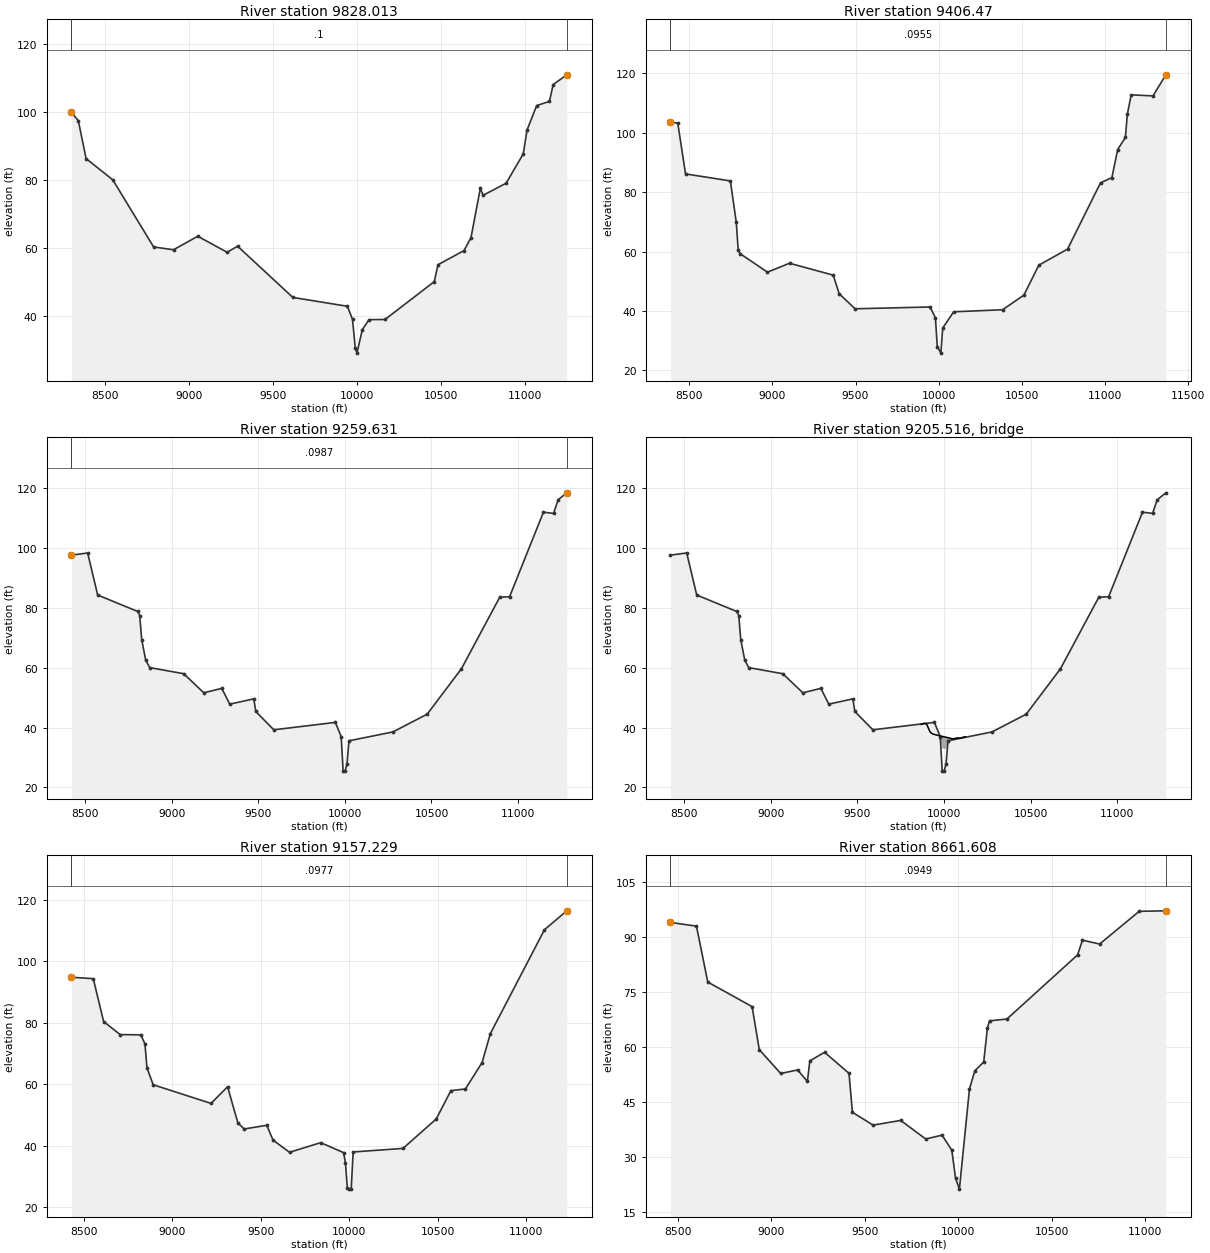
Type RM Length L Ch R = 1 ,9828.013,421.543100,421.543100,421.543100
XS GIS Cut Line= 6
747261.622135043861147.714396402747357.298244298860869.005730331
747586.088940293859962.162607849747740.498676509859644.211076021
747992.521357894859276.710547581748403.642369092858452.243813097
#Sta/Elev= 30
8299.984100.03128341.18797.476128387.43786.341858546.02980.102878789.65560.30269
8908.18959.470249052.57663.457459227.90358.720359289.78360.528769618.98945.41691
9944.41742.807269974.56538.923339990.95230.48124   10001 28.998310032.8435.90257
10072.5838.8658910168.2938.9212710461.9250.0882710483.5555.0470510638.8259.23762
10680.3263.0187410735.9777.5685310752.7575.5339710889.47 79.075810991.93 87.7488
11014.19 94.745511071.77101.980911147.74103.2146   11170108.170611250.97111.0432
#Mann= 3 , 0 , 0
8299.984     0.1       08299.984     0.1       011250.97     0.1       0
#XS Ineff= 2 , 0
       0                               0
Bank Sta=8299.984,11250.97
Exp/Cntr=0.3,0.1

Type RM Length L Ch R = 1 , 9406.47,146.838200,146.838200,146.838200
XS GIS Cut Line= 6
747309.794961156861172.674677732747611.262892254860681.779178293
748024.318064907860040.672225692 748099.56793485859902.893284263
748292.275555706859509.800975186 748814.73066853858606.095801489
#Sta/Elev= 30
8387.562103.66888431.469103.24338478.08786.166178747.61283.811578782.98869.91035
8794.77960.376628806.571 59.29378970.48953.078419103.19556.086359366.06252.07646
9401.908 45.78679497.49640.747679947.57841.355669980.36437.701089991.293 28.0434
10013.1125.8134910024.0234.2765510090.0239.7337510384.0940.42455   1051245.34204
 10601.955.4358710774.6760.8514810972.6583.1657511041.1684.9220211075.9294.38173
11122.2798.4408411133.86106.197211157.03112.790711288.49112.443711365.29119.5385
#Mann= 3 , 0 , 0
8387.562  0.0955       08387.562  0.0955       011365.29  0.0955       0
#XS Ineff= 2 , 0
       0                               0
Bank Sta=8387.562,11365.29
Exp/Cntr=0.3,0.1

Type RM Length L Ch R = 1 ,9259.631,102.402500,102.402500,102.402500
XS GIS Cut Line= 4
747497.726728886861226.123162135748217.039711803859985.999267966
748317.137185365859788.383717597 748933.95401901858752.202848628
#Sta/Elev= 30
8420.50797.688948514.28998.400898572.09184.33985  8803.378.838228814.86177.49218
8826.42169.398638849.54262.546978872.66360.06514 9069.1958.018029184.79551.63563
9288.83953.116479335.08147.836959473.80649.612719485.36645.38422 9589.4139.25609
9944.94341.737239978.57236.983059989.78225.5946610000.9925.43449 10012.227.79716
10023.41 35.574710277.4438.5455510475.2944.4823610673.1359.6858910894.2483.58897
10951.2483.7767211146.74112.050111205.39111.648611231.73116.198611281.54118.5265
#Mann= 3 , 0 , 0
8420.507  0.0987       08420.507  0.0987       011281.54  0.0987       0
#XS Ineff= 2 , 0
       0                               0
Bank Sta=8420.507,11281.54
Exp/Cntr=0.3,0.1

Type RM Length L Ch R = 3 ,9205.516,,,
BEGIN DESCRIPTION:
END DESCRIPTION:
Bridge Culvert--1,0,-1,-1, 0
Deck Dist Width WeirC Skew NumUp NumDn MinLoCord MaxHiCord MaxSubmerge Is_Ogee
11.667200,79.068100,2.6,0, 28, 28, , , 0.95, 0, 0,0,,
 9868.38 9873.26 9883.86 9894.47 9897.92 9905.07 9915.68 9917.24 9926.45 9926.66
 9937.26 9947.66 9966.37 9966.3710031.0110031.0110051.3110056.1310058.5810066.93
10077.7410084.9710088.5510099.3510110.1610111.3510120.9610122.92
   41.07   41.13   41.42   41.33   41.30   40.49   39.08   38.83   38.16   38.16
   37.83   37.65   37.39   37.39   36.51   36.51   36.23   36.27   36.29   36.38
   36.57   36.53   36.46   36.46   36.77   36.79   36.91   36.93
 -958.93 -958.87 -958.58 -958.67 -958.70 -959.51 -960.92 -961.17 -961.84 -961.84
 -962.17 -962.35 -962.61   33.39   32.51 -963.49 -963.77 -963.73 -963.71 -963.62
 -963.43 -963.47 -963.54 -963.54 -963.23 -963.21 -963.09 -963.07
 9868.38 9873.26 9883.86 9894.47 9897.92 9905.07 9915.68 9917.24 9926.45 9926.66
 9937.26 9947.66 9967.84 9967.8410032.4710032.4710051.3110056.1310058.5810066.93
10077.7410084.9710088.5510099.3510110.1610111.3510120.9610122.92
   41.07   41.13   41.42   41.33   41.30   40.49   39.08   38.83   38.16   38.16
   37.83   37.65   37.37   37.37   36.49   36.49   36.23   36.27   36.29   36.38
   36.57   36.53   36.46   36.46   36.77   36.79   36.91   36.93
 -958.93 -958.87 -958.58 -958.67 -958.70 -959.51 -960.92 -961.17 -961.84 -961.84
 -962.17 -962.35 -962.63   33.37   32.49 -963.51 -963.77 -963.73 -963.71 -963.62
 -963.43 -963.47 -963.54 -963.54 -963.23 -963.21 -963.09 -963.07
BR Coef=-1 , 0 , 0 ,, 0 ,,,0.8,0,1,0,
WSPro=,,,, 1 ,,,, 0 ,,,, 0 ,,,,-1 ,-1 ,-1 , 0 , 0 , 0 , 0 , 0
BC Design=,, 0 ,, 0 ,,,,,,

Type RM Length L Ch R = 1 ,9157.229,495.620800,495.620800,495.620800
XS GIS Cut Line= 4
747584.413704753861250.777256176748314.589281529860044.153819174
748442.033018738859742.411495402749003.901543707858837.922854364
#Sta/Elev= 30
 8428.4494.821248552.07794.348538610.51980.410278704.02776.159028820.91176.07795
8844.28873.174748855.97665.291158891.04259.838759218.31853.771319311.82559.18215
9370.26747.441379405.333 45.44979533.90546.647869568.97141.837069662.47837.86584
9838.79440.999159968.35837.754279978.99534.35484 9989.8526.0896110000.7125.87937
10011.5626.0123110022.4237.9726310304.5739.1288310492.9348.7292510575.3357.92094
10657.7458.4709510751.9267.0593110799.0176.5059911105.09110.287811231.14116.4288
#Mann= 3 , 0 , 0
 8428.44  0.0977       0 8428.44  0.0977       011231.14  0.0977       0
#XS Ineff= 2 , 0
       0                               0
Bank Sta=8428.44,11231.14
Exp/Cntr=0.3,0.1

Type RM Length L Ch R = 1 ,8661.608,395.298300,395.298300,395.298300
XS GIS Cut Line= 6
747645.381524163861268.116727755748013.675254126860773.766315508
748336.372968318860414.485057045748548.061249194860249.718114408
748926.387456178860096.695434961749503.511350438859450.189774436
#Sta/Elev= 30
 8461.0993.91555 8600.1392.90768 8660.5277.684988897.70470.99143 8935.9459.28265
9050.64852.785859140.90653.748089193.29950.638629206.47456.233779285.52258.56223
9415.90952.819039434.15542.220789544.63238.729689692.44240.003759826.34134.94505
9913.64536.003089965.67531.911229986.05124.2200410006.3921.2957610060.3248.63005
10089.2853.5387310136.3755.9054710155.9165.0908710167.5567.1222410260.3867.61427
10638.3385.0748510664.7689.1004410756.4288.0335410967.9396.9467811110.4297.08293
#Mann= 3 , 0 , 0
 8461.09  0.0949       0 8461.09  0.0949       011110.42  0.0949       0
#XS Ineff= 2 , 0
       0                               0
Bank Sta=8461.09,11110.42
Exp/Cntr=0.3,0.1

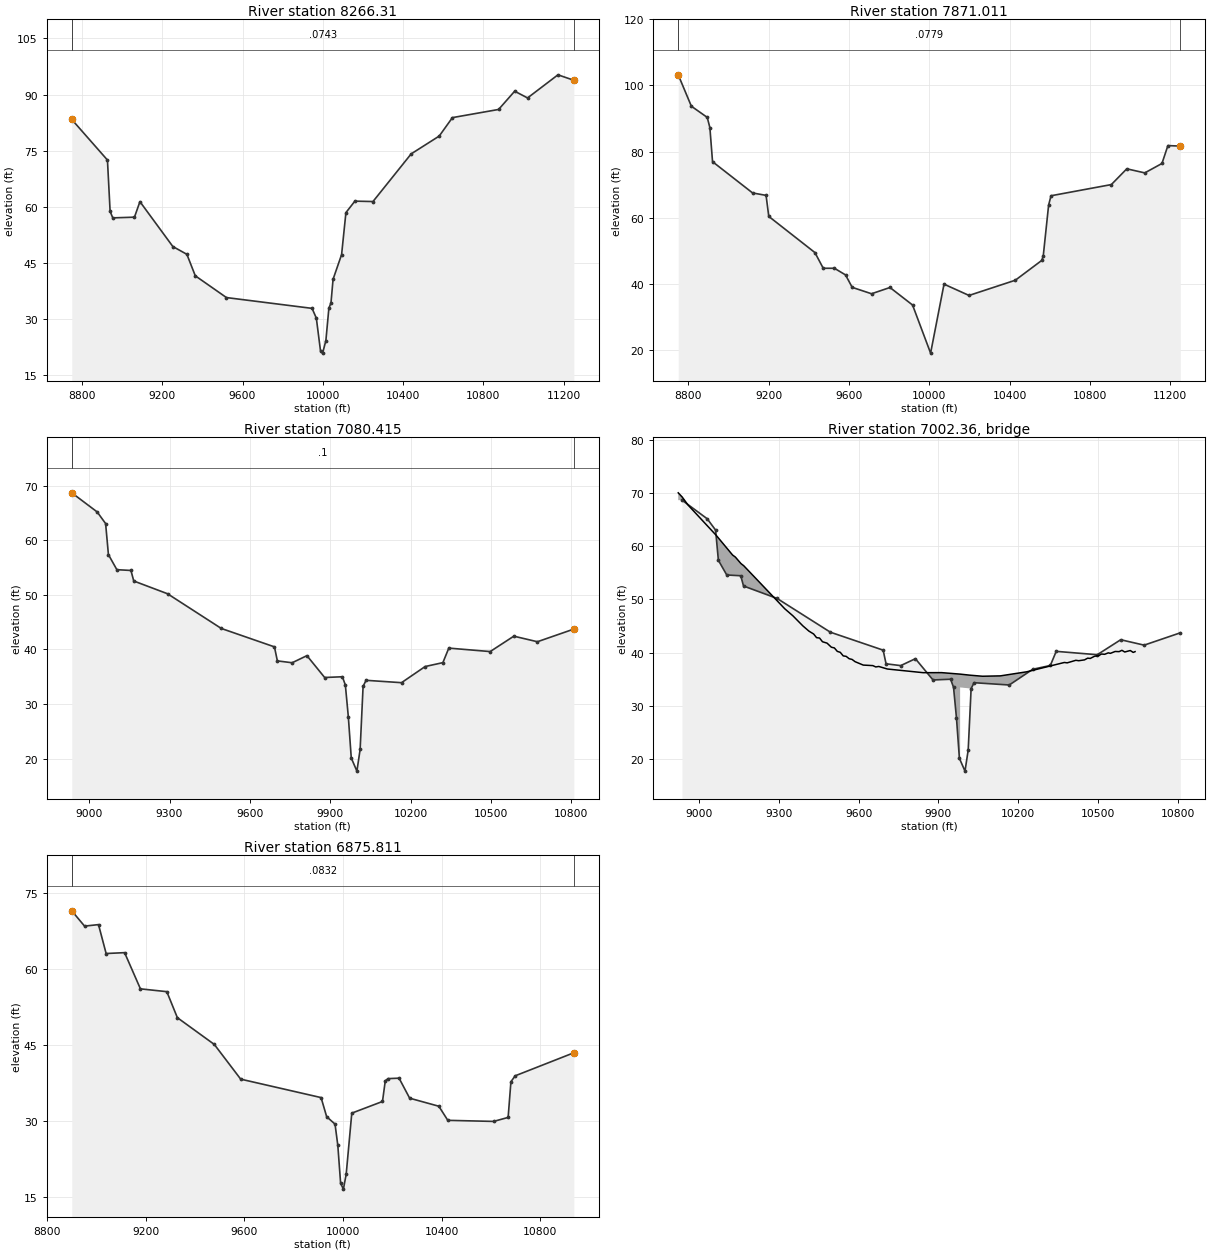
Type RM Length L Ch R = 1 , 8266.31,395.298400,395.298400,395.298400
XS GIS Cut Line= 6
748152.036970938861378.886305605748468.324043456861026.589456499
748904.778159508 860582.85901111749011.382262662860324.575024585
749067.542919888860228.936868181749706.119843618859442.225293806
#Sta/Elev= 30
8749.11783.322198926.91272.462088940.19258.720598953.47156.984939061.53857.17396
9088.74361.328539252.791 49.31429322.70347.23132 9364.6541.477769519.92135.65268
9946.53432.763159967.77230.148869988.65821.350769999.06620.7835610015.3424.15017
10030.3132.8359810040.7334.2088310051.1440.5497910093.6747.1631110115.1858.39248
10159.85 61.464210250.0161.35529 10440.474.1179910580.0678.8819410645.9183.82085
10875.9486.0027610956.1290.8901511020.28 89.085911171.6795.2723111250.9193.81736
#Mann= 3 , 0 , 0
8749.117  0.0743       08749.117  0.0743       011250.91  0.0743       0
#XS Ineff= 2 , 0
       0                               0
Bank Sta=8749.117,11250.91
Exp/Cntr=0.3,0.1

Type RM Length L Ch R = 1 ,7871.011,790.596700,790.596700,790.596700
XS GIS Cut Line= 6
748233.916489831861594.549022379748905.893305397860865.167167025
749051.454248823860754.611158512749320.263385855860615.677496813
 749466.38360742 860496.20221573 750002.08758378859856.691791149
#Sta/Elev= 30
8749.091103.19498814.45693.714418893.608 90.3371  8906.887.237278919.99276.95828
9119.63567.509749186.78966.777469200.21960.424589430.25149.492929471.65744.75435
9527.23244.758029582.80642.747079615.83438.993299712.32437.057869804.17538.94822
9916.70333.6538410006.6119.1203610073.4839.9582810198.0636.5458310428.7441.14346
10560.9147.1455510568.1948.6028210594.6963.8406910606.6566.6619710907.2770.04026
10984.2474.8021111073.8573.5695311159.47 76.416611189.07 81.814811250.9181.66978
#Mann= 3 , 0 , 0
8749.091  0.0779       08749.091  0.0779       011250.91  0.0779       0
#XS Ineff= 2 , 0
       0                               0
Bank Sta=8749.091,11250.91
Exp/Cntr=0.3,0.1

Type RM Length L Ch R = 1 ,7080.415,204.603500,204.603500,204.603500
XS GIS Cut Line= 5
748824.725032548861443.781289997749282.393211156861296.146393672
749541.942740917861182.116356507750329.268211156860814.375560358
750548.534672689860713.175655043
#Sta/Elev= 30
8935.05968.670119029.915 65.16799061.43763.039289071.94457.346999103.46754.59011
9156.00454.448069166.51152.51773  9292.650.183069493.38443.824789691.86140.45036
9702.81837.880889758.00337.541379813.188 38.84149879.41134.837439945.63334.97693
 9956.6733.460749967.70727.692599978.74420.09462 9999.8217.6874110011.8621.65938
10022.8933.2090510033.9334.3235410166.3733.8905210254.6736.8498210320.8937.56336
10342.9740.2233910497.48 39.590110585.7442.4102710673.8541.3913710809.9143.70988
#Mann= 3 , 0 , 0
8935.059     0.1       08935.059     0.1       010809.91     0.1       0
#XS Ineff= 2 , 0
       09858.594        10243.46       0
Bank Sta=8935.059,10809.91
Exp/Cntr=0.3,0.1

Type RM Length L Ch R = 3 , 7002.36,,,
BEGIN DESCRIPTION:
END DESCRIPTION:
Bridge Culvert--1,0,-1,-1, 0
Deck Dist Width WeirC Skew NumUp NumDn MinLoCord MaxHiCord MaxSubmerge Is_Ogee
60.143050,84.317400,2.6,0, 60, 60, , , 0.95, 0, 0,0,,
 8920.90 8936.12 8957.15 9064.14 9125.34 9135.85 9156.88 9167.39 9321.76 9352.31
 9389.89 9412.60 9430.27 9441.41 9452.55 9463.69 9480.74 9497.10 9508.24 9519.38
 9530.51 9541.65 9552.79 9563.93 9575.06 9586.20 9617.01 9653.03 9664.17 9675.30
 9707.86 9842.37 9911.72 9981.46 9981.4610018.5410018.5410065.8410132.9310232.52
10373.5010384.3510416.8810427.7310449.4210461.3210471.1110487.1710503.6410513.01
10525.3310538.8510547.0210564.6910579.5610590.2210600.8410621.5810632.7010639.64
   70.05   69.24   67.79   62.03   58.35   57.96   56.74   56.33   48.23   46.91
   45.01   44.03   43.49   42.80   42.73   42.03   41.77   41.00   40.87   40.22
   40.04   39.37   39.28   38.84   38.70   38.28   37.64   37.54   37.29   37.38
   36.90   36.21   36.22   35.94   35.94   35.74   35.74   35.54   35.61   36.38
   38.13   38.06   38.54   38.46   38.62   38.94   38.89   39.30   39.43   39.72
   39.67   39.94   39.85   40.20   40.17   40.42   40.10   40.38   40.02   40.17
 -929.95 -930.76 -932.21 -937.97 -941.65 -942.04 -943.26 -943.67 -951.77 -953.09
 -954.99 -955.97 -956.51 -957.20 -957.27 -957.97 -958.23 -959.00 -959.13 -959.78
 -959.96 -960.63 -960.72 -961.16 -961.30 -961.72 -962.36 -962.46 -962.71 -962.62
 -963.10 -963.79 -963.78 -964.06   33.44   33.24 -964.26 -964.46 -964.39 -963.62
 -961.87 -961.94 -961.46 -961.54 -961.38 -961.06 -961.11 -960.70 -960.57 -960.28
 -960.33 -960.06 -960.15 -959.80 -959.83 -959.58 -959.90 -959.62 -959.98 -959.83
 8920.90 8936.12 8957.15 9064.14 9125.34 9135.85 9156.88 9167.39 9321.76 9352.31
 9389.89 9412.60 9430.27 9441.41 9452.55 9463.69 9480.74 9497.10 9508.24 9519.38
 9530.51 9541.65 9552.79 9563.93 9575.06 9586.20 9617.01 9653.03 9664.17 9675.30
 9707.86 9842.37 9911.72 9981.46 9981.4610018.5410018.5410065.8410132.9310232.52
10373.5010384.3510416.8810427.7310449.4210461.3210471.1110487.1710503.6410513.01
10525.3310538.8510547.0210564.6910579.5610590.2210600.8410621.5810632.7010639.64
   70.05   69.24   67.79   62.03   58.35   57.96   56.74   56.33   48.23   46.91
   45.01   44.03   43.49   42.80   42.73   42.03   41.77   41.00   40.87   40.22
   40.04   39.37   39.28   38.84   38.70   38.28   37.64   37.54   37.29   37.38
   36.90   36.21   36.22   35.94   35.94   35.74   35.74   35.54   35.61   36.38
   38.13   38.06   38.54   38.46   38.62   38.94   38.89   39.30   39.43   39.72
   39.67   39.94   39.85   40.20   40.17   40.42   40.10   40.38   40.02   40.17
 -929.95 -930.76 -932.21 -937.97 -941.65 -942.04 -943.26 -943.67 -951.77 -953.09
 -954.99 -955.97 -956.51 -957.20 -957.27 -957.97 -958.23 -959.00 -959.13 -959.78
 -959.96 -960.63 -960.72 -961.16 -961.30 -961.72 -962.36 -962.46 -962.71 -962.62
 -963.10 -963.79 -963.78 -964.06   33.44   33.24 -964.26 -964.46 -964.39 -963.62
 -961.87 -961.94 -961.46 -961.54 -961.38 -961.06 -961.11 -960.70 -960.57 -960.28
 -960.33 -960.06 -960.15 -959.80 -959.83 -959.58 -959.90 -959.62 -959.98 -959.83
BR Coef=-1 , 0 , 0 ,, 0 ,,,0.8,0,1,0,
WSPro=,,,, 1 ,,,, 0 ,,,, 0 ,,,,-1 ,-1 ,-1 , 0 , 0 , 0 , 0 , 0
BC Design=,, 0 ,, 0 ,,,,,,

Type RM Length L Ch R = 1 ,6875.811,487.863300,487.863300,487.863300
XS GIS Cut Line= 5
748904.789044499861663.333893672749582.449092388861406.926094547
750102.359407604861132.116356492750358.833819717861031.474498585
750676.464971587860717.956585346
#Sta/Elev= 30
 8901.1971.400478952.99768.390899009.51268.68603 9040.4162.991259115.25363.16281
9179.40556.033589286.32455.479599329.09150.354939478.77845.086469585.69738.24864
9911.39734.618379934.019 30.85479967.95229.393029979.26325.182239990.57417.73498
10001.8916.58839 10013.219.5450110035.8231.5532610160.2433.8512810171.5537.92242
10182.8638.3504210227.3938.4433910270.36 34.496210388.5232.9144210424.9230.13608
10610.3929.9245810669.3630.7103810680.6537.7383710697.8338.9049610935.6243.44471
#Mann= 3 , 0 , 0
 8901.19  0.0832       0 8901.19  0.0832       010935.62  0.0832       0
#XS Ineff= 2 , 0
       09884.848        10266.43       0
Bank Sta=8901.19,10935.62
Exp/Cntr=0.3,0.1