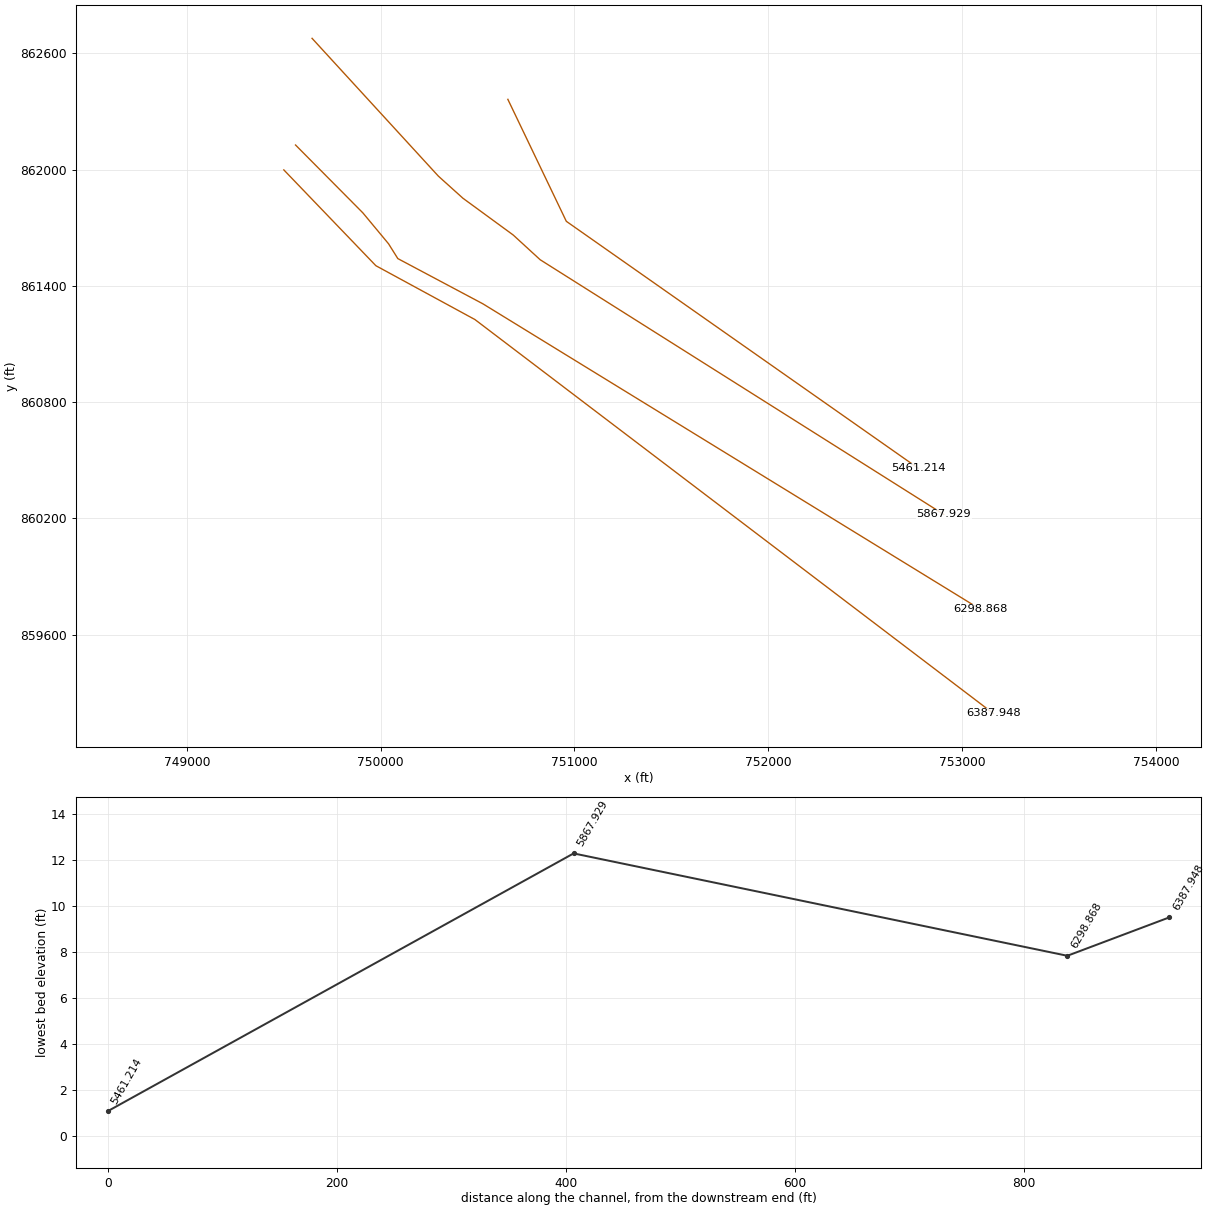
HEC-RAS study 15242_ras.prj: 15242

--- 15242_ras.g01 (geometry) --- (continued)

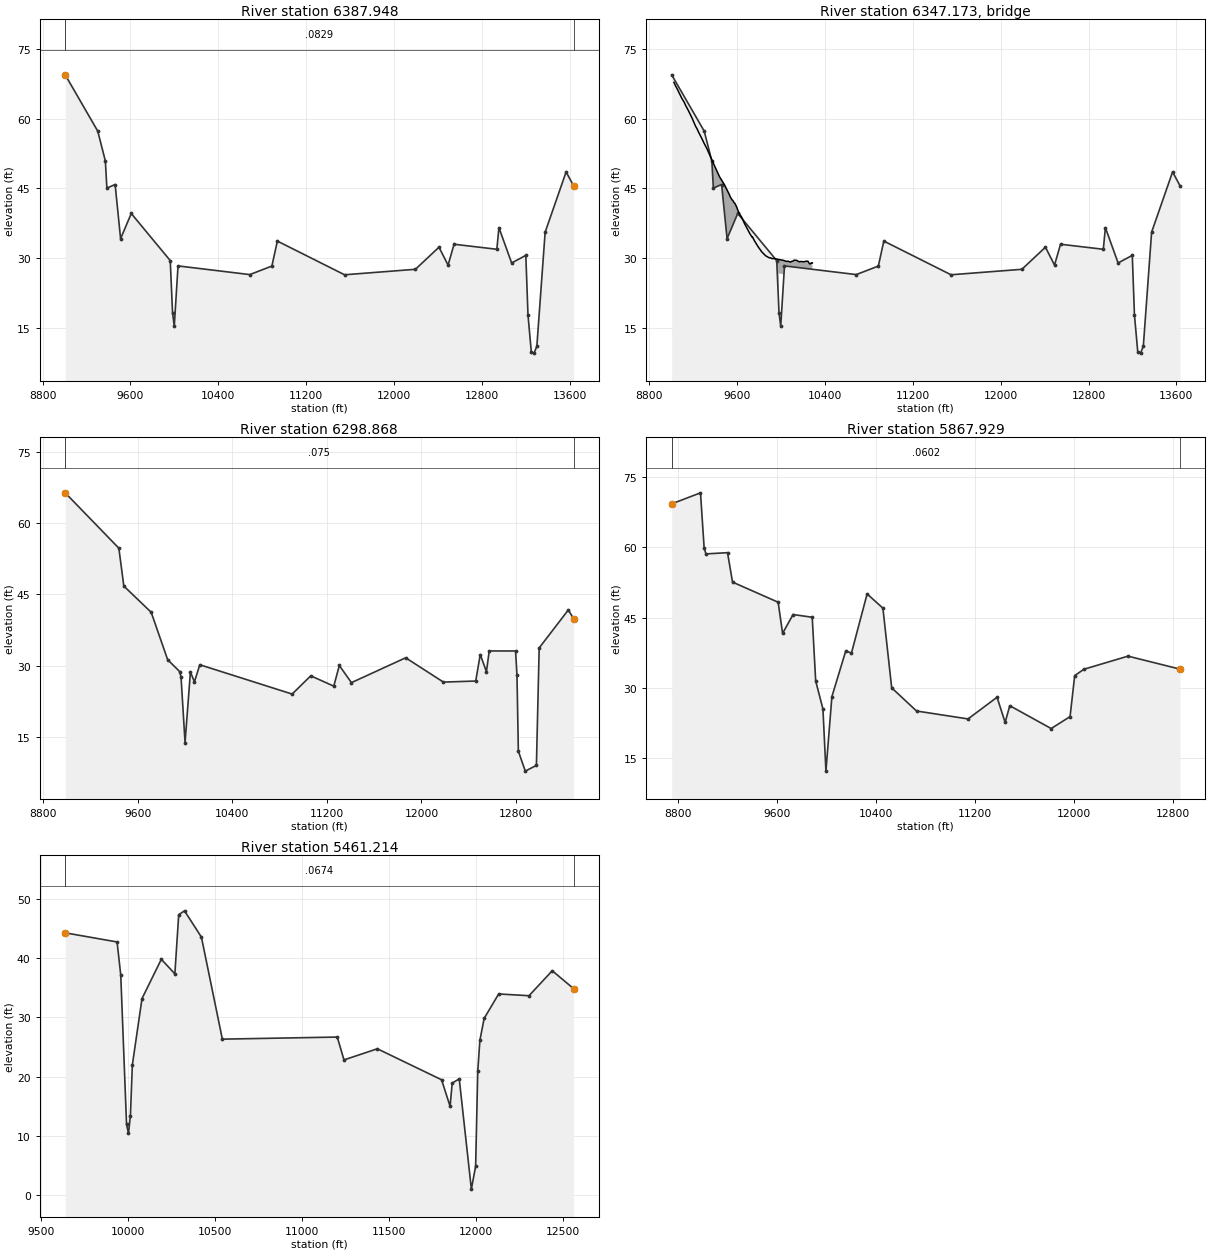
Type RM Length L Ch R = 1 ,6387.948,89.079700,89.079700,89.079700
XS GIS Cut Line= 4
749500.304847956861998.534546524749975.304847926861504.090102077
 750486.41595903  861226.3123243753160.712689489   859194.210143
#Sta/Elev= 30
9006.426 69.48159302.531 57.35299371.86550.913359385.73245.064579460.67245.84651
9510.53334.167929607.60139.601159962.40229.448259983.34418.148159999.016 15.3223
10033.1628.3031510686.4626.4316810887.4228.2708510937.0933.6545911548.6526.39228
 12193.627.5715312408.1332.3375212490.7728.4702212545.2632.97407 12934.631.88649
12953.5736.5484413069.2728.9396213198.3530.5714613218.0317.7473313248.599.667997
13273.719.50678113298.8311.0115913374.1835.5721613565.1348.5627313632.5545.57875
#Mann= 3 , 0 , 0
9006.426  0.0829       09006.426  0.0829       013632.55  0.0829       0
#XS Ineff= 2 , 0
       0                10286.63       0
Bank Sta=9006.426,13632.55
Exp/Cntr=0.3,0.1

Type RM Length L Ch R = 3 ,6347.173,,,
BEGIN DESCRIPTION:
END DESCRIPTION:
Bridge Culvert--1,0,-1,-1, 0
Deck Dist Width WeirC Skew NumUp NumDn MinLoCord MaxHiCord MaxSubmerge Is_Ogee
26.495250,36.089200,2.6,0, 58, 58, , , 0.95, 0, 0,0,,
 9027.04 9041.24 9054.33 9097.43 9119.78 9132.87 9159.05 9190.42 9224.50 9237.59
 9250.68 9283.40 9298.89 9328.04 9386.83 9442.33 9485.19 9528.04 9540.86 9556.62
 9564.65 9570.15 9582.73 9595.31 9619.08 9645.61 9668.55 9718.07 9739.61 9742.74
 9759.73 9793.69 9827.64 9861.59 9895.55 9907.37 9918.18 9940.82 9978.67 9978.67
10021.3310021.3310053.9910065.3110087.9410099.5710110.5810120.9210142.2810167.17
10178.4810212.4410227.7010246.7610259.1510264.7910282.8210286.72
   67.87   67.13   66.57   64.47   63.60   62.91   61.75   60.23   58.37   57.84
   57.15   55.64   54.85   53.53   50.37   47.50   45.86   43.84   43.14   42.53
   42.37   42.07   41.74   41.13   39.68   38.72   37.46   35.25   34.44   34.51
   33.72   32.41   31.29   30.49   30.03   30.04   29.88   29.88   29.70   29.70
   29.51   29.51   29.26   29.32   29.12   29.29   29.34   29.55   29.51   29.19
   29.25   29.20   29.31   29.31   28.82   28.71   29.01   28.94
 -932.13 -932.87 -933.43 -935.53 -936.40 -937.09 -938.25 -939.77 -941.63 -942.16
 -942.85 -944.36 -945.15 -946.47 -949.63 -952.50 -954.14 -956.16 -956.86 -957.47
 -957.63 -957.93 -958.26 -958.87 -960.32 -961.28 -962.54 -964.75 -965.56 -965.49
 -966.28 -967.59 -968.71 -969.51 -969.97 -969.96 -970.12 -970.12 -970.30   26.70
   26.51 -970.49 -970.74 -970.68 -970.88 -970.71 -970.66 -970.45 -970.49 -970.81
 -970.75 -970.80 -970.69 -970.69 -971.18 -971.29 -970.99 -971.06
 9027.04 9041.24 9054.33 9097.43 9119.78 9132.87 9159.05 9190.42 9224.50 9237.59
 9250.68 9283.40 9298.89 9328.04 9386.83 9442.33 9485.19 9528.04 9540.86 9556.62
 9564.65 9570.15 9582.73 9595.31 9619.08 9645.61 9668.55 9718.07 9739.61 9742.74
 9759.73 9793.69 9827.64 9861.59 9895.55 9907.37 9918.18 9940.82 9978.67 9978.67
10021.3310021.3310053.9910065.3110087.9410099.5710110.5810120.9210142.2810167.17
10178.4810212.4410227.7010246.7610259.1510264.7910282.8210286.72
   67.87   67.13   66.57   64.47   63.60   62.91   61.75   60.23   58.37   57.84
   57.15   55.64   54.85   53.53   50.37   47.50   45.86   43.84   43.14   42.53
   42.37   42.07   41.74   41.13   39.68   38.72   37.46   35.25   34.44   34.51
   33.72   32.41   31.29   30.49   30.03   30.04   29.88   29.88   29.70   29.70
   29.51   29.51   29.26   29.32   29.12   29.29   29.34   29.55   29.51   29.19
   29.25   29.20   29.31   29.31   28.82   28.71   29.01   28.94
 -932.13 -932.87 -933.43 -935.53 -936.40 -937.09 -938.25 -939.77 -941.63 -942.16
 -942.85 -944.36 -945.15 -946.47 -949.63 -952.50 -954.14 -956.16 -956.86 -957.47
 -957.63 -957.93 -958.26 -958.87 -960.32 -961.28 -962.54 -964.75 -965.56 -965.49
 -966.28 -967.59 -968.71 -969.51 -969.97 -969.96 -970.12 -970.12 -970.30   26.70
   26.51 -970.49 -970.74 -970.68 -970.88 -970.71 -970.66 -970.45 -970.49 -970.81
 -970.75 -970.80 -970.69 -970.69 -971.18 -971.29 -970.99 -971.06
BR Coef=-1 , 0 , 0 ,, 0 ,,,0.8,0,1,0,
WSPro=,,,, 1 ,,,, 0 ,,,, 0 ,,,,-1 ,-1 ,-1 , 0 , 0 , 0 , 0 , 0
BC Design=,, 0 ,, 0 ,,,,,,

Type RM Length L Ch R = 1 ,6298.868,430.939300,430.939300,430.939300
XS GIS Cut Line= 6
749560.721514583862127.006768748749907.943736792861777.006768733
750040.629527003 861617.36380823750088.499292374861540.895657629
750527.388181269861307.562324315753092.512660414859732.232595086
#Sta/Elev= 30
8987.55166.391279441.13454.740429483.17546.775059714.53441.259079853.681 31.2858
9955.60928.780399966.93527.6371610000.9113.8480710046.2128.7007810080.1926.61481
10125.4930.2178910906.3324.0495211063.7727.8895711258.3825.7154711305.3230.06202
11407.7326.4530411866.3431.6838312185.4726.56645 12458.726.7916312496.9232.36769
12549.2628.7589612572.73 33.1196 12795.733.1163912807.4427.9903712819.1712.03118
12877.857.83445412971.73 9.04816 12995.233.7601713241.64 41.755513285.6639.92298
#Mann= 3 , 0 , 0
8987.551   0.075       08987.551   0.075       013285.66   0.075       0
#XS Ineff= 2 , 0
       0                10314.24       0
Bank Sta=8987.551,13285.66
Exp/Cntr=0.3,0.1

Type RM Length L Ch R = 1 ,5867.929,406.714500,406.714500,406.714500
XS GIS Cut Line= 6
749646.023998857862677.335281208750297.814424574861966.277937576
750424.454173058 861852.29801698750683.931052029  861662.5395789
750823.062784553861534.940633595752905.353264898860220.877935588
#Sta/Elev= 30
8749.04569.196538981.98371.548569011.28859.87755 9025.9458.542889200.44358.80686
9240.67952.544059609.44148.254869645.46441.627039730.16445.635269884.85945.05004
9912.86731.481379971.41425.524479995.58112.2895310043.8328.1496610155.7137.88002
10201.9237.4328210328.4450.0228410456.0546.9928910526.9930.0234110728.02 25.0914
11144.0323.4037311378.3828.0185111443.8322.6617411481.3126.2219811815.8921.35781
11968.4923.8980612005.96 32.629912080.9233.9875512436.9336.7742912856.8934.00788
#Mann= 3 , 0 , 0
8749.045  0.0602       08749.045  0.0602       012856.89  0.0602       0
#XS Ineff= 2 , 0
       0                10370.78       0
Bank Sta=8749.045,12856.89
Exp/Cntr=0.3,0.1

Type RM Length L Ch R = 1 ,5461.214,0.000000,0.000000,0.000000
XS GIS Cut Line= 3
750656.321825743862362.521866009750957.971131295861733.181588218
          752775860458.197625294
#Sta/Elev= 30
9640.68144.224249938.391 42.68869959.52437.109299992.79211.9758410003.8810.46205
10014.9713.4620710026.0621.9842610081.5133.16184 10192.439.7707110270.0337.32398
 10292.247.2837310325.4747.9305610422.4643.5067310542.6226.32397 11202.326.67497
11240.7222.8270111432.2324.70231 11800.919.4834111849.7615.0117111861.9818.92463
 11902.319.6349411971.921.06903811996.364.91838112008.5720.9036412020.7926.10427
12045.2229.8156812128.6233.9327512302.7233.6361612436.1437.84021 12558.334.83842
#Mann= 3 , 0 , 0
9640.681  0.0674       09640.681  0.0674       0 12558.3  0.0674       0
#XS Ineff= 2 , 0
       0                10350.91       0
Bank Sta=9640.681,12558.3
Exp/Cntr=0.3,0.1